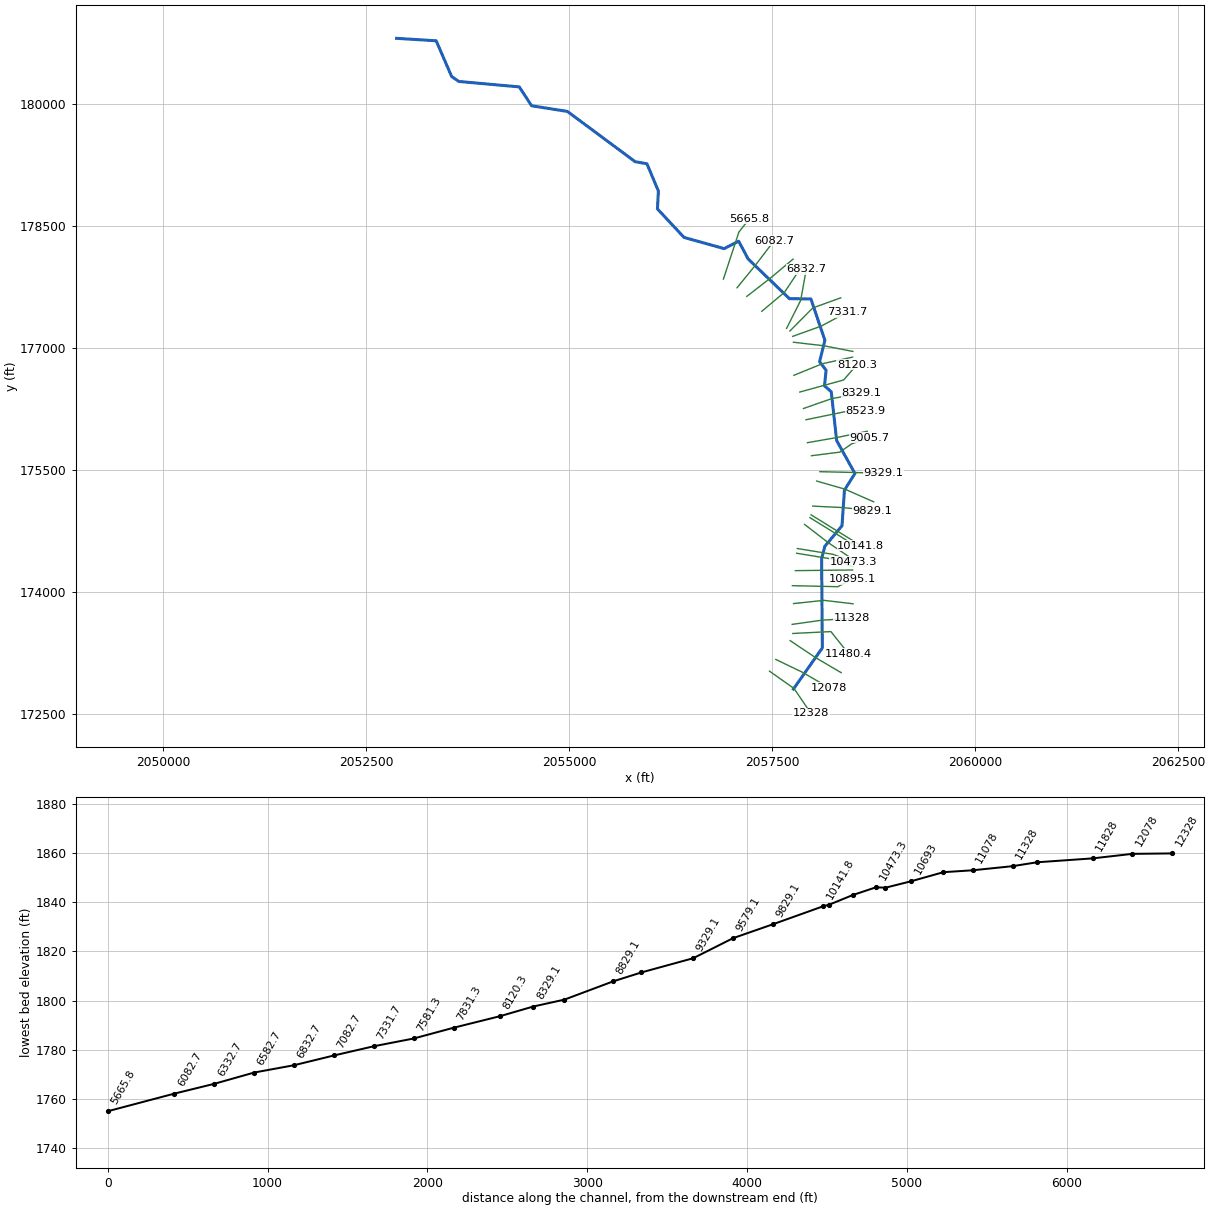
--- BLLKCK.prj (project) ---

Proj Title=BLLKCK
Current Plan=p01
Default Exp/Contr=0,0
English Units
Geom File=g01
Flow File=f01
Plan File=p01
BEGIN DESCRIPTION:
END DESCRIPTION:
DSS Export Rating Curves= 0
DSS Export Rating Curve Sorted= 0
DSS Export Volume Flow Curves= 0
DXF OffsetX= 0
DXF OffsetY= 0
DXF ScaleX= 0
DXF ScaleY= 0

--- BLLKCK.p01 (plan) ---

Plan Title=Floodplain
Program Version=4.00
Geom File=g01
Flow File=f01
K Sum by GR=0
Std Step Tol=0.01
Critical Tol=0.01
Num of Std Step Trials=20
Max Error Tol=0.3
Flow Tol Ratio=0.001
Split Flow NTrial=30
Split Flow Tol=0.02
Split Flow Ratio=0.02
Log Output Level=0
Friction Slope Method=1
Unsteady Friction Slope Method=2
Unsteady Bridges Friction Slope Method=1
Global Log Level=0
CheckData=False
Run HTab=0
Run UNet=0
Run PostProcess=0
UNET Theta=0
UNET Theta Warmup=0
UNET ZTol=0
UNET ZSATol=0
UNET MxIter=0
UNET MaxInSteps=0
UNET DtIC=0
UNET DtMin=0
UNET MaxCRTS=0
UNET WFStab=0
UNET SFStab=0
UNET WFX=0
UNET SFX=0
UNET DSS MLevel=0
UNET DZMax Abort=0
UNET Convert EG Bridges=0
UNET Use Existing IB Tables=0
UNET Froude Limit=0
UNET Froude Power=0
Write IC File=0
Echo Input=False
Echo Output=False
Write Detailed=0

--- BLLKCK.f01 (steady flow) ---

Flow Title=2010 USGS WV Regression Equation
Program Version=5.03
Number of Profiles= 1
Profile Names=P100yr
River Rch & RM=BLLKCK,Main            ,12328
525.1283
River Rch & RM=BLLKCK,Main            ,11328
581.5949
River Rch & RM=BLLKCK,Main            ,9579.1
645.0183
River Rch & RM=BLLKCK,Main            ,7581.3
715.0703
River Rch & RM=BLLKCK,Main            ,4332.7
 792.726
River Rch & RM=BLLKCK,Main            ,4082.7
1179.471
River Rch & RM=BLLKCK,Main            ,444.8
1218.313
River Rch & RM=BLLKCK,Main            ,80
1218.792
Boundary for River Rch & Prof#=BLLKCK,Main            , 1
Up Type= 0
Dn Type= 3
Dn Slope=0.0097
DSS Import GetInterval= 0
DSS Import GetPeak= 0
DSS Import FillOption= 0

--- BLLKCK.g01 (geometry) ---

Geom Title=LiDAR
Program Version=4.10

River Reach=BLLKCK          ,Main
Reach XY= 30
      2057762.87      172803.274     2058118.425      173309.524
     2058109.901      174409.694     2058149.675      174560.219
     2058360.786      174812.302     2058390.821      175251.625
     2058519.945      175455.618      2058294.93      175861.651
      2058228.22      176462.085     2058144.925      176535.603
     2058165.199      176726.148      2058084.47      176831.356
     2058150.095      177095.939     2057977.699      177604.272
     2057713.636      177607.397     2057204.782      178096.981
      2057088.81      178314.978     2056910.338      178223.312
     2056416.366      178361.173     2056088.582      178712.038
     2056100.388       178932.09     2055959.416      179267.507
     2055813.481      179293.896     2054980.249      179911.951
      2054539.87      179981.396     2054387.193      180214.035
     2053644.138      180280.701     2053555.249      180341.118
     2053364.971      180781.396      2052877.64        180811.5

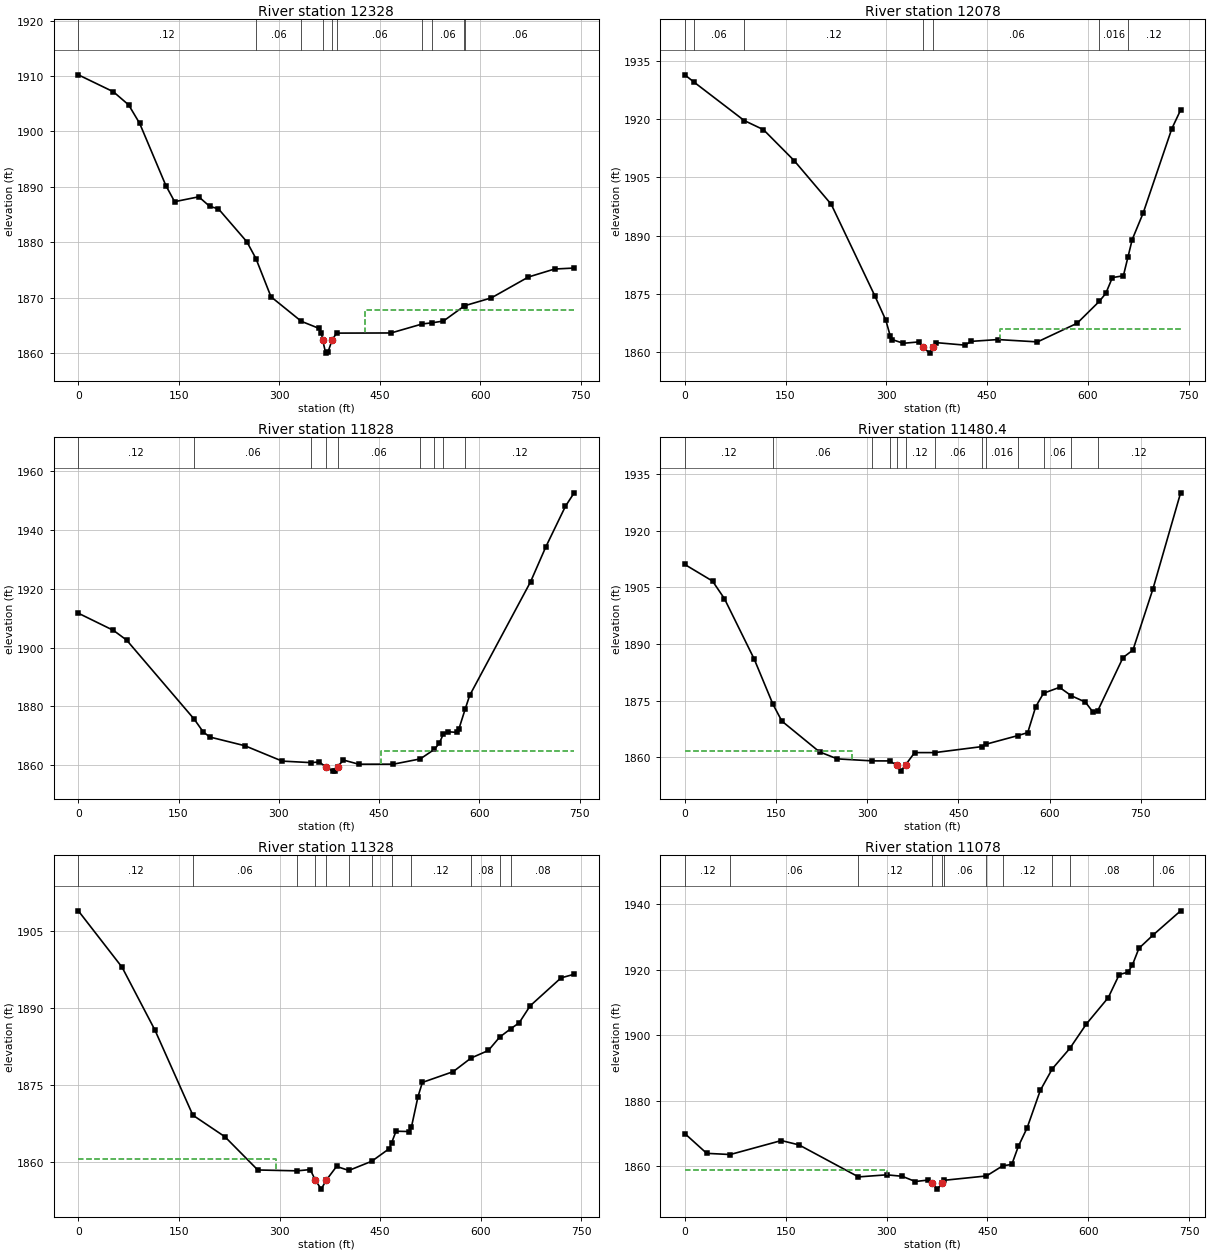
Type RM Length L Ch R = 1 ,12328   ,245,250,259.7
XS GIS Cut Line= 3
     2057468.313      173023.148     2057769.941      172810.345
     2057978.494      172503.782
#Sta/Elev= 30
       0 1910.22    52.3 1907.16    75.1 1904.79    91.5 1901.46   130.7 1890.21
   143.7 1887.32   179.7  1888.2     196 1886.48   209.1 1886.02   251.5 1880.08
  265.031877.055   287.5 1870.15   332.71865.727   359.3 1864.44   362.6 1863.67
   364.61862.355   369.1 1859.98   372.4 1860.12   378.9 1862.42  385.441863.593
   466.7 1863.62   513.3 1865.25  527.551865.449   544.8 1865.77  575.211868.424
  577.151868.559   616.3 1869.95   671.6 1873.72   710.6 1875.16   739.9 1875.34
#Mann= 10 ,-1 , 0
       0     .12       0  265.03     .06       0   332.7     .12       0
   364.6    .045       0   378.9     .12       0  385.44     .06       0
   513.3     .08       0  527.55     .06       0  575.21     .08       0
  577.15     .06       0
#XS Ineff= 2 , 0
                          428.48         1867.85
Permanent Ineff=
       F       F
Bank Sta=364.6,378.9
XS Rating Curve= 0 ,0
Exp/Cntr=0.3,0.1

Type RM Length L Ch R = 1 ,12078   ,253.4,250,249.3
XS GIS Cut Line= 3
     2057545.926      173167.613     2057874.156      173009.371
     2058197.353      172821.656
#Sta/Elev= 30
       0 1931.39   12.961929.615   88.44 1919.63   117.1 1917.28   162.7 1909.34
     218 1898.08     283  1874.5   299.3 1868.24   305.8 1864.22   309.1 1863.27
   325.3 1862.33   348.1 1862.68   354.6 1861.36   364.4  1859.8  370.221861.374
   374.2  1862.5   416.8 1861.86   426.7 1862.83     466 1863.29     525 1862.69
     584 1867.48  617.011873.113   626.7 1875.17   636.5 1879.23   652.9  1879.7
  659.611884.447     666    1889   682.4 1895.87     725 1917.54   738.1 1922.34
#Mann= 7 ,-1 , 0
       0     .12       0   12.96     .06       0   88.44     .12       0
   354.6    .045       0  370.22     .06       0  617.01    .016       0
  659.61     .12       0
#XS Ineff= 2 , 0
                          469.76         1866.11
Permanent Ineff=
       F       F
Bank Sta=354.6,370.22
XS Rating Curve= 0 ,0
Exp/Cntr=0.3,0.1

Type RM Length L Ch R = 1 ,11828   ,332.5,347.6,360.3
XS GIS Cut Line= 3
     2057722.172      173399.382     2058038.379      173187.901
     2058350.409      173005.221
#Sta/Elev= 30
       0 1911.67    52.5 1905.83    72.2 1902.54  173.541875.586   186.9 1871.28
   196.8 1869.55   249.2 1866.59     305 1861.36  347.761860.844   360.7 1861.06
   370.6 1859.31   380.4 1857.95   383.7 1857.98   387.9 1859.43   396.7 1861.72
   419.5 1860.31   471.6 1860.32   511.71862.107  532.611865.312     540 1867.36
  545.931870.412     553 1871.34   566.1 1871.14   569.3 1872.14  578.731878.917
   585.6 1883.68   676.8 1922.37   699.6 1934.24     729 1948.06     742 1952.62
#Mann= 9 ,-1 , 0
       0     .12       0  173.54     .06       0  347.76     .12       0
   370.6    .045       0   387.9     .06       0   511.7     .12       0
  532.61     .06       0  545.93    .016       0  578.73     .12       0
#XS Ineff= 2 , 0
                          452.43         1864.73
Permanent Ineff=
       F       F
Bank Sta=370.6,387.9
XS Rating Curve= 0 ,0
Exp/Cntr=0.3,0.1

Type RM Length L Ch R = 1 ,11480.4 ,149.3,152.4,151.2
XS GIS Cut Line= 3
     2057755.348      173487.099     2058224.098      173510.536
     2058440.011       173239.77
#Sta/Elev= 30
       0 1911.04    45.6 1906.65    65.2 1901.99   114.1 1886.03  144.991874.056
   159.7 1869.59   221.6 1861.45     251  1859.6  308.081859.072  336.891859.058
   348.3 1857.98   355.3 1856.36   363.3 1858.06   378.1 1861.26  411.141861.261
  488.23 1862.84  495.281863.473  547.531865.748   564.1 1866.55   577.2 1873.38
  590.051876.966   616.4 1878.53  635.891876.292   658.8 1874.64   671.9 1871.89
  679.351872.359   720.9 1886.42   737.2  1888.4   769.9 1904.48   815.6    1930
#Mann= 13 ,-1 , 0
       0     .12       0  144.99     .06       0  308.08     .08       0
  336.89     .12       0   348.3    .045       0   363.3     .12       0
  411.14     .06       0  488.23     .12       0  495.28    .016       0
  547.53     .12       0  590.05     .06       0  635.89    .016       0
  679.35     .12       0
#XS Ineff= 2 , 0
          275.54 1861.76
Permanent Ineff=
       F       F
Bank Sta=348.3,363.3
XS Rating Curve= 0 ,0
Exp/Cntr=0.3,0.1

Type RM Length L Ch R = 1 ,11328   ,250.2,250,245
XS GIS Cut Line= 3
     2057747.448      173599.016      2058105.93      173649.793
     2058482.367      173673.582
#Sta/Elev= 30
       0 1908.85    65.2 1897.89   114.2 1885.68  170.761869.145   218.5 1864.96
   267.5  1858.5   326.31858.331   345.8 1858.58  353.23 1856.54   362.1 1854.78
   369.6 1856.52     385 1859.19  403.25 1858.41  437.471860.198   463.7 1862.66
  467.071863.779   473.6 1866.03   493.3 1865.97  496.661866.866   506.4 1872.76
   512.9 1875.51   558.8  1877.6  585.461880.248   611.3 1881.72  628.161884.313
  644.361885.908   657.2 1887.09   673.6 1890.39   719.6 1895.82   739.2 1896.53
#Mann= 12 ,-1 , 0
       0     .12       0  170.76     .06       0   326.3     .12       0
  353.23    .045       0   369.6     .12       0  403.25     .06       0
  437.47     .12       0  467.07    .016       0  496.66     .12       0
  585.46     .08       0  628.16    .016       0  644.36     .08       0
#XS Ineff= 2 , 0
          294.74 1860.54
Permanent Ineff=
       F       F
Bank Sta=353.23,369.6
XS Rating Curve= 0 ,0
Exp/Cntr=0.3,0.1

Type RM Length L Ch R = 1 ,11078   ,185.8,182.9,184.9
XS GIS Cut Line= 3
     2057764.722      173855.056      2058138.02      173894.826
     2058497.526       173852.53
#Sta/Elev= 30
       0 1870.05    32.6 1864.01   67.52 1863.65   143.6 1867.91   169.8 1866.59
  258.321856.829   300.3 1857.46   323.2 1857.02   342.8 1855.42   362.4 1855.88
   367.9 1854.86   375.4  1853.1   382.9 1854.86  385.221855.784  448.611857.116
  472.961860.228   486.3 1860.62   496.1 1866.17   509.1 1871.78   528.7 1883.21
   546.61889.805  572.61 1896.01   597.2 1903.45   629.8  1911.5   646.1 1918.52
   659.1 1919.25   665.6 1921.41   675.4 1926.53  696.711930.631   737.4 1937.96
#Mann= 11 ,-1 , 0
       0     .12       0   67.52     .06       0  258.32     .12       0
   367.9    .045       0   382.9     .12       0  385.22     .06       0
  448.61    .016       0  472.96     .12       0   546.6     .06       0
  572.61     .08       0  696.71     .06       0
#XS Ineff= 2 , 0
          300.17 1858.94
Permanent Ineff=
       F       F
Bank Sta=367.9,382.9
XS Rating Curve= 0 ,0
Exp/Cntr=0.3,0.1

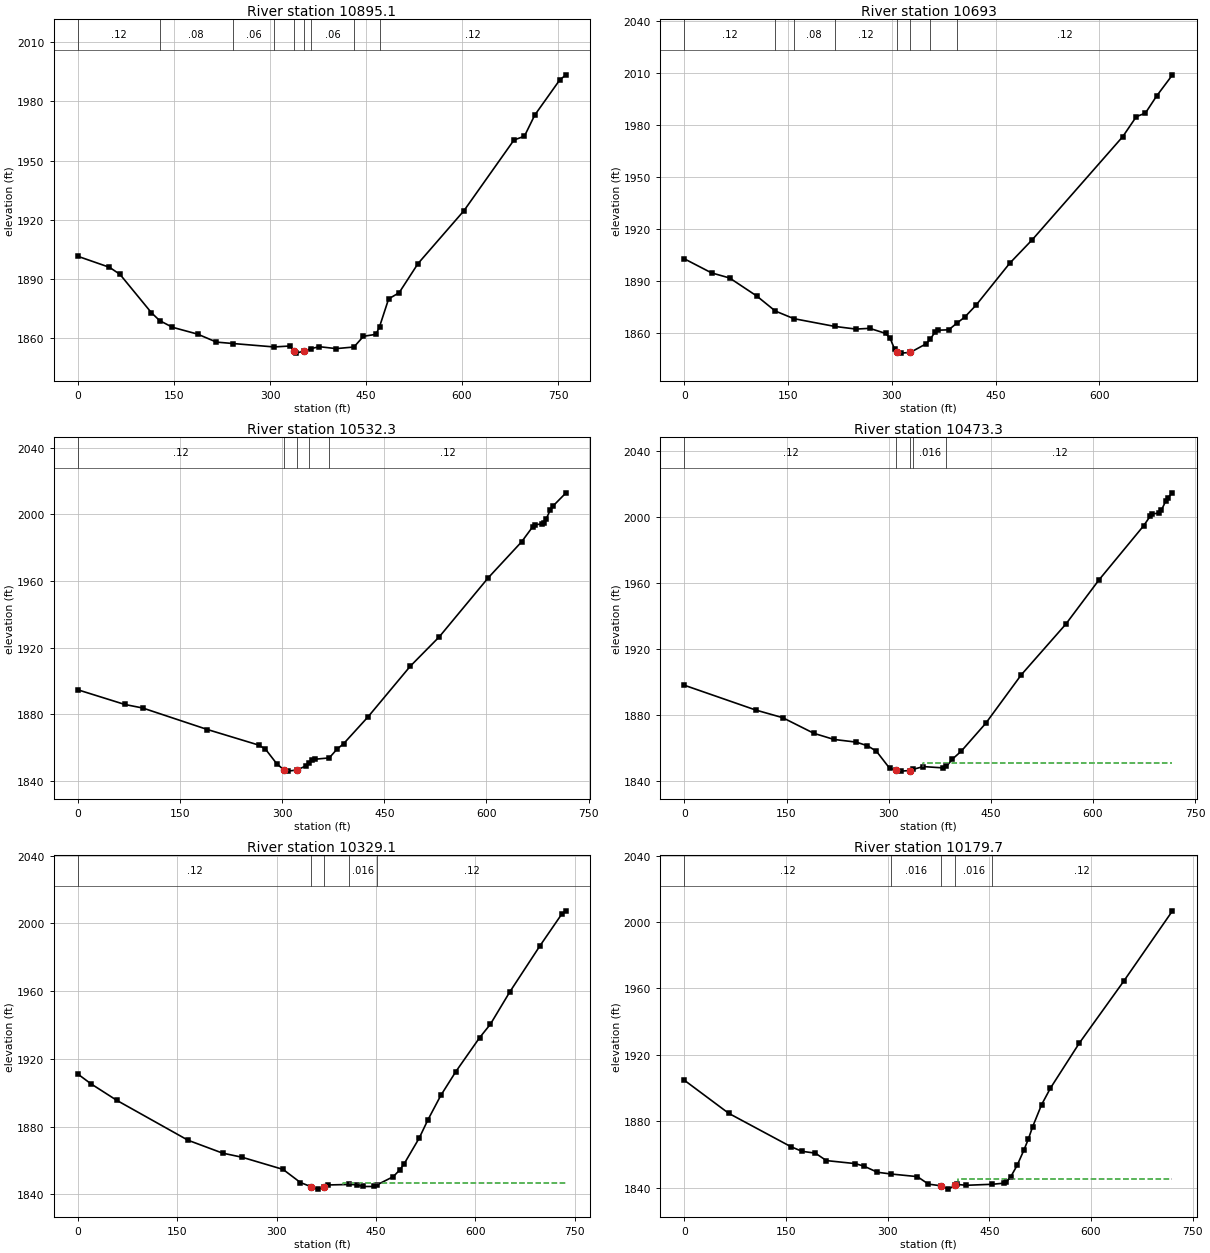
Type RM Length L Ch R = 1 ,10895.1 ,201.1,202.1,202.6
XS GIS Cut Line= 3
     2057750.139       174075.64     2058307.431      174062.619
     2058489.723      174156.369
#Sta/Elev= 30
       0 1901.43    49.2 1895.87    65.6  1892.3   114.8 1872.82  127.541868.847
   147.6 1865.44   186.9 1861.97   216.4 1857.92  242.22  1857.2   306.31855.466
   331.2 1855.94     338 1853.39     341 1852.33     353 1853.42  364.121854.609
   377.1 1855.59   403.3 1854.62  431.151855.436     446 1860.87   465.6 1861.87
  471.081865.709   485.3 1879.85   501.7 1882.96   531.2 1897.76     603 1924.59
   681.1 1960.43   697.4 1962.36   713.6 1973.09   752.7 1990.94   762.4 1993.49
#Mann= 9 ,-1 , 0
       0     .12       0  127.54     .08       0  242.22     .06       0
   306.3     .12       0     338    .045       0     353     .12       0
  364.12     .06       0  431.15    .016       0  471.08     .12       0
Bank Sta=338,353
XS Rating Curve= 0 ,0
Exp/Cntr=0.3,0.1

Type RM Length L Ch R = 1 ,10693   ,164.7,160.8,156.9
XS GIS Cut Line= 2
     2057786.598      174260.536     2058492.327      174268.349
#Sta/Elev= 30
       0 1902.95    39.2 1894.87    65.4 1891.92   104.6 1881.54  131.36  1872.9
  158.26 1868.49  217.341864.023   248.3 1862.48   267.9 1862.92   290.8 1860.01
   297.3 1857.31   303.9    1851   306.9 1849.29   313.7 1848.63   326.8 1849.06
   349.6 1854.02   355.61856.681   362.7 1860.96     366 1861.82   382.3 1862.07
  393.491865.751   405.2 1869.32   421.5 1876.15   470.5 1900.46   503.2 1914.05
   633.9 1973.38   653.5 1984.88   666.6 1986.92   682.9 1996.81   705.8 2008.98
#Mann= 8 ,-1 , 0
       0     .12       0  131.36     .06       0  158.26     .08       0
  217.34     .12       0   306.9    .045       0   326.8     .12       0
   355.6    .016       0  393.49     .12       0
Bank Sta=306.9,326.8
XS Rating Curve= 0 ,0
Exp/Cntr=0.3,0.1

Type RM Length L Ch R = 1 ,10532.3 ,59,59,59
XS GIS Cut Line= 3
     2057802.825      174474.316     2058242.785      174402.398
     2058496.571      174307.471
#Sta/Elev= 30
       0 1894.76    68.8 1885.98    95.1 1883.86   190.1 1870.96   265.5 1861.62
   275.4 1859.19   291.7 1850.57  302.741846.618   308.1    1846   321.2 1846.64
   334.4 1849.05  339.171850.615   344.2 1852.59   347.5 1853.11  369.071853.936
   380.2 1859.05   390.1 1862.43   426.1 1878.59   488.2 1908.99   530.7 1926.58
   602.5 1961.93   651.5 1983.51   667.8 1992.53     671 1993.76   680.8 1994.24
   684.1 1995.12   687.4  1997.1   693.9 2002.79   697.2 2004.81   716.8 2012.92
#Mann= 5 ,-1 , 0
       0     .12       0  302.74    .045       0   321.2     .12       0
  339.17    .016       0  369.07     .12       0
Bank Sta=302.74,321.2
XS Rating Curve= 0 ,0
Exp/Cntr=0.3,0.1

Type RM Length L Ch R = 1 ,10473.3 ,155.3,144.2,134.3
XS GIS Cut Line= 3
     2057810.305      174532.872     2058250.265      174460.954
     2058504.051      174366.027
#Sta/Elev= 30
       0 1898.17   104.9 1883.15   144.2 1878.56   190.1 1869.07   219.6 1865.36
   252.4 1863.73   268.8 1861.53   281.9 1858.26   301.6 1847.77   311.4 1846.64
     318 1846.17   331.1 1846.52  336.391847.296   350.7 1848.92   380.2 1848.12
   384.71848.974   393.4 1853.39   406.5 1858.22   442.5 1875.11   494.8 1904.54
   560.1 1935.16     609 1962.06   674.3  1994.7   684.1  2000.6   687.4 2001.89
   697.2 2002.52   700.4 2004.15     707 2009.79   710.2 2011.86   716.8 2014.71
#Mann= 5 ,-1 , 0
       0     .12       0   311.4    .045       0   331.1     .12       0
  336.39    .016       0   384.7     .12       0
#XS Ineff= 2 , 0
                          350.58         1851.21
Permanent Ineff=
       F       F
Bank Sta=311.4,331.1
XS Rating Curve= 0 ,0
Exp/Cntr=0.3,0.1

Type RM Length L Ch R = 1 ,10329.1 ,146.8,149.4,150.3
XS GIS Cut Line= 3
     2057899.811      174829.401     2058186.549      174608.373
     2058496.663      174397.327
#Sta/Elev= 30
       0 1910.96    19.6 1905.26    58.7 1895.47   166.3 1871.91   218.5  1864.3
   247.9 1861.87   309.8 1854.69     336 1846.94   352.2 1844.46     362 1843.04
   371.8 1844.39   378.4  1845.5  409.161845.792   420.8 1845.64   430.5  1844.6
   446.8  1844.6   451.41845.503   476.2 1850.39     486 1854.34   492.5 1857.86
   515.4 1873.16   528.4 1883.82     548 1898.34   570.8 1912.48   606.7 1932.51
     623 1940.46   652.4  1959.6     698 1986.85   730.6  2005.4   737.2 2007.41
#Mann= 5 ,-1 , 0
       0     .12       0   352.2    .045       0   371.8     .12       0
  409.16    .016       0   451.4     .12       0
#XS Ineff= 2 , 0
                          400.82         1846.85
Permanent Ineff=
       F       F
Bank Sta=352.2,371.8
XS Rating Curve= 0 ,0
Exp/Cntr=0.3,0.1

Type RM Length L Ch R = 1 ,10179.7 ,38.1,37.9,38.1
XS GIS Cut Line= 2
     2057965.417      174912.793     2058578.264      174534.321
#Sta/Elev= 30
       0 1904.62    65.5  1884.7   157.2 1864.62   173.5 1861.85   193.2 1860.75
   209.5 1856.26   252.1 1854.44   265.2 1852.88   284.8 1849.23  305.411848.159
   343.8  1846.6   360.2 1842.07   379.2 1841.06   389.6 1839.07   399.4 1841.34
   402.7  1841.9   415.8 1841.38  454.121841.992   471.5 1842.64   474.7 1843.25
   481.3  1846.3   491.1 1853.44   500.9 1862.48   507.5 1869.15     514 1876.74
   527.1 1889.92   540.2 1899.92   582.8 1927.03   648.3 1964.29   720.3 2006.69
#Mann= 5 ,-1 , 0
       0     .12       0  305.41    .016       0   379.2    .045       0
   399.4    .016       0  454.12     .12       0
#XS Ineff= 2 , 0
                          403.26         1844.88
Permanent Ineff=
       F       F
Bank Sta=379.2,399.4
XS Rating Curve= 0 ,0
Exp/Cntr=0.3,0.1

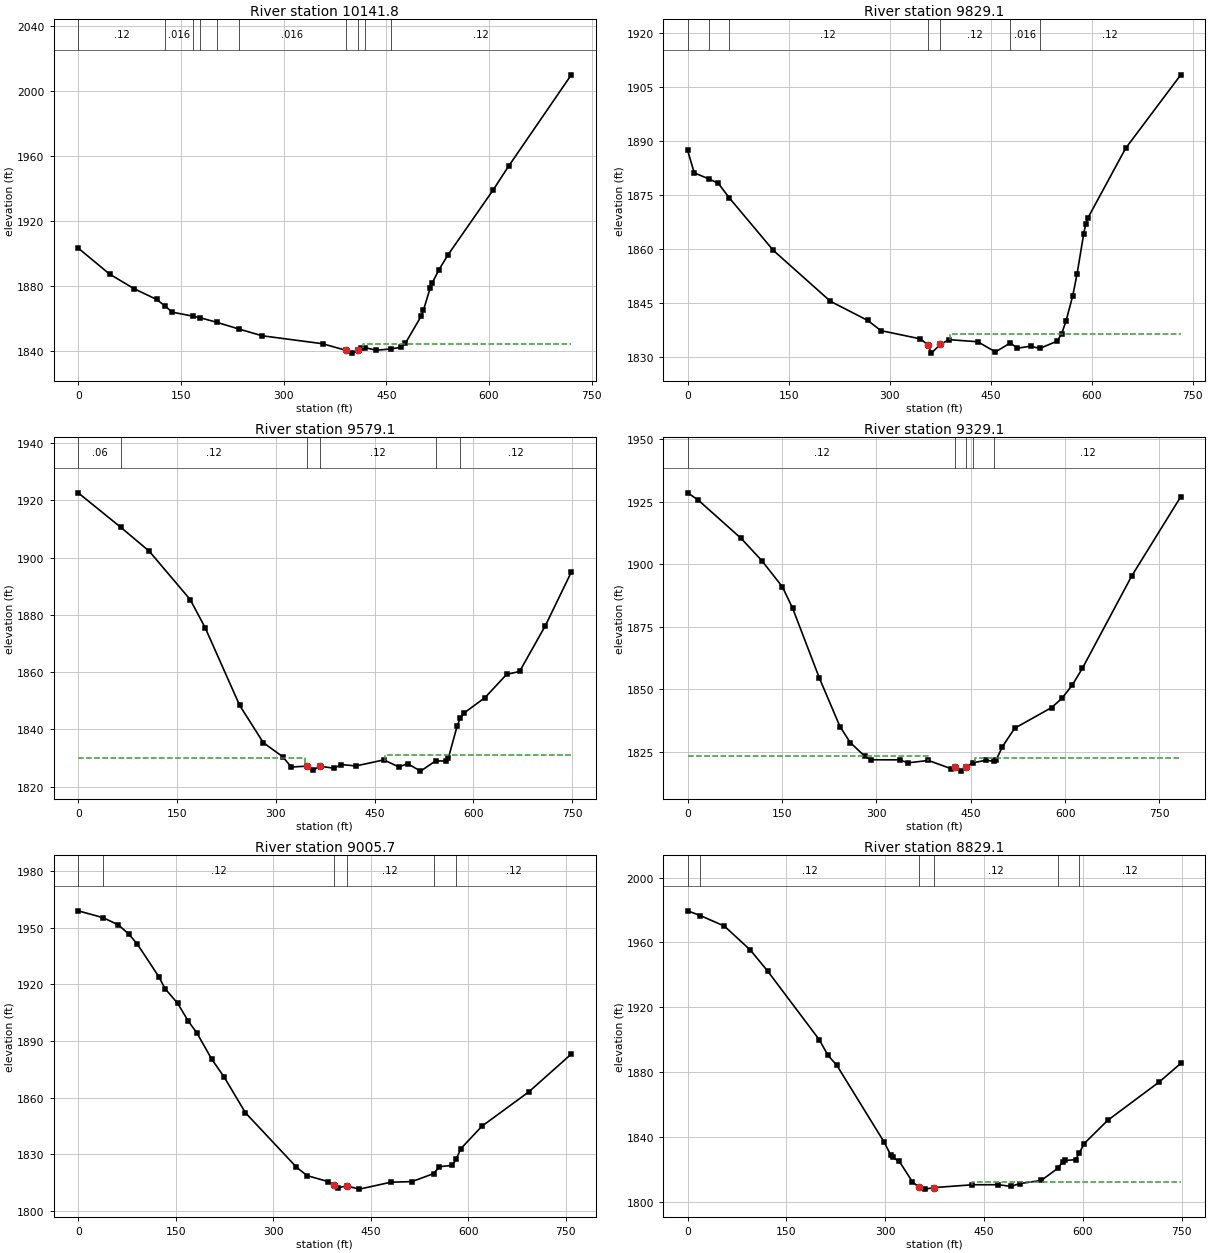
Type RM Length L Ch R = 1 ,10141.8 ,300.6,312.8,322.5
XS GIS Cut Line= 2
     2057979.306      174947.515     2058592.153      174569.043
#Sta/Elev= 30
       0 1903.17    45.8 1887.15    81.8 1878.08   114.6  1871.5  126.511867.559
   137.5 1863.65  167.771861.195  178.341860.192  202.491857.416  234.551853.311
   268.5 1849.13   356.9 1844.22  390.571840.204   399.4 1838.42   409.3 1840.13
   412.5 1841.57  418.441841.862   435.4  1840.2  456.79 1841.01   471.5 1842.04
     478 1844.56   500.9 1861.14   504.2  1864.7     514 1878.33   517.3 1881.82
   527.1 1889.89   540.2    1899   605.7  1938.7   628.6 1953.56   720.3 2009.95
#Mann= 10 ,-1 , 0
       0     .12       0  126.51    .016       0  167.77     .06       0
  178.34    .016       0  202.49     .08       0  234.55    .016       0
  390.57    .045       0   409.3     .12       0  418.44    .016       0
  456.79     .12       0
#XS Ineff= 2 , 0
                          416.52         1843.88
Permanent Ineff=
       F       F
Bank Sta=390.57,409.3
XS Rating Curve= 0 ,0
Exp/Cntr=0.3,0.1

Type RM Length L Ch R = 1 ,9829.1  ,252.9,250,243.6
XS GIS Cut Line= 3
     2058001.452      175054.619     2058366.191      175036.569
     2058731.292      175000.076
#Sta/Elev= 30
       0 1887.32     9.8  1881.1   32.011879.382    45.6 1878.18   61.581874.211
   127.2  1859.6   211.9  1845.5   267.4 1840.17   286.9 1837.36   345.6 1835.07
  356.251833.473   361.9 1831.12     375 1833.52   388.1 1834.85   430.7 1834.28
   456.9 1831.45  479.081833.929   489.7 1832.48   509.3 1833.06  522.521832.409
   548.6 1834.44   555.2 1836.47   561.8 1840.05   571.6 1846.92   578.1 1853.02
     588  1864.2   591.2 1867.05   594.5 1868.69   650.2 1887.89   732.1 1908.28
#Mann= 7 ,-1 , 0
       0    .016       0   32.01     .06       0   61.58     .12       0
  356.25    .045       0     375     .12       0  479.08    .016       0
  522.52     .12       0
#XS Ineff= 2 , 0
                          389.38         1836.35
Permanent Ineff=
       F       F
Bank Sta=356.25,375
XS Rating Curve= 0 ,0
Exp/Cntr=0.3,0.1

Type RM Length L Ch R = 1 ,9579.1  ,244.1,250,258.2
XS GIS Cut Line= 3
     2058048.659       175362.83     2058394.372      175264.053
     2058750.646      175107.312
#Sta/Elev= 30
       0 1922.58   64.851910.512   107.9  1902.2     170 1885.34   192.8 1875.51
   245.2 1848.38   281.1 1835.38   310.5 1830.48   323.6 1826.87  347.771827.185
   356.3 1825.71     367 1827.15     389 1826.43   398.8 1827.74   421.7 1827.25
   464.2 1829.36   487.1 1826.87   500.2 1828.05   519.8 1825.44  542.631828.973
   559.1    1829   562.3 1830.16   575.4 1841.13  580.061843.933   585.2  1845.6
   617.9 1851.13   650.6 1859.22   670.3 1860.23   709.5 1876.24   748.8 1894.91
#Mann= 6 ,-1 , 0
       0     .06       0   64.85     .12       0  347.77    .045       0
     367     .12       0  542.63    .016       0  580.06     .12       0
#XS Ineff= 2 , 0
          343.77 1830.05  466.51         1831.17
Permanent Ineff=
       F       F
Bank Sta=347.77,367
XS Rating Curve= 0 ,0
Exp/Cntr=0.3,0.1

Type RM Length L Ch R = 1 ,9329.1  ,308.4,323.4,337.4
XS GIS Cut Line= 3
      2058088.58        175478.3     2058520.368       175468.33
      2058872.19      175456.604
#Sta/Elev= 30
       0 1928.65    16.4 1925.84    85.1 1910.39   117.8 1901.52   150.5 1891.05
   166.9 1882.45   209.4 1854.49   242.1  1835.1   258.5 1828.68   281.4 1823.25
   291.2  1821.8     337 1821.76   350.1 1820.56   382.8 1821.52   418.8 1818.23
   425.4 1818.79   435.2 1817.25   441.7 1818.89  453.741820.607   474.3  1821.6
  487.081821.179   490.6 1821.81   500.4 1827.05   519.9 1834.42   578.6  1842.7
   594.9 1846.35   611.2  1851.6   627.5 1858.39   705.7 1895.26   783.9 1927.09
#Mann= 5 ,-1 , 0
       0     .12       0   425.4    .045       0   441.7     .12       0
  453.74    .016       0  487.08     .12       0
#XS Ineff= 2 , 0
          382.22 1823.23  456.59         1822.63
Permanent Ineff=
       F       F
Bank Sta=425.4,441.7
XS Rating Curve= 0 ,0
Exp/Cntr=0.3,0.1

Type RM Length L Ch R = 1 ,9005.7  ,186.5,176.6,167.2
XS GIS Cut Line= 4
     2057984.514      175674.599     2058333.473      175718.869
     2058479.306      175820.432     2058695.452      175895.953
#Sta/Elev= 30
       0 1958.99   38.151955.367    61.9 1951.52    78.2 1946.53    91.2 1941.22
   123.8 1924.17   133.5 1917.76   153.1  1909.9   169.4 1900.48   182.4 1894.34
   205.2 1880.46   224.7 1870.75   257.3 1851.92   335.5 1823.18   351.8 1818.66
   384.1 1815.49   393.8  1813.4   400.2 1812.27   413.2 1813.15   432.5 1811.47
     481 1815.14   513.3 1815.46  546.561819.688   555.6 1823.39   575.3 1824.03
  581.141827.196   588.3 1832.86     621 1844.83     693 1863.01   758.4 1883.07
#Mann= 6 ,-1 , 0
       0     .06       0   38.15     .12       0   393.8    .045       0
   413.2     .12       0  546.56    .016       0  581.14     .12       0
Bank Sta=393.8,413.2
XS Rating Curve= 0 ,0
Exp/Cntr=0.3,0.1

Type RM Length L Ch R = 1 ,8829.1  ,304.4,305.2,305.3
XS GIS Cut Line= 3
     2057935.664      175835.357     2058290.892      175897.466
     2058671.064      175975.457
#Sta/Elev= 30
       0 1979.48   19.071976.589    55.7 1970.07    95.1 1955.33   121.3 1942.41
     200  1899.9   213.1 1890.28   226.2 1884.38   298.3 1836.86   308.2 1828.98
   311.4 1827.35   321.3 1824.99     341  1812.5   350.8 1809.06   360.6 1807.84
   373.7 1808.78   432.4 1810.53   471.5 1810.56   491.1 1809.54   504.1 1811.24
   536.7 1813.17  562.471820.808   569.3 1824.71   572.6  1825.5   588.9 1825.99
  594.611830.037     602  1835.9   637.8 1850.28   716.1 1873.96   748.7 1885.39
#Mann= 6 ,-1 , 0
       0     .08       0   19.07     .12       0   350.8    .045       0
   373.7     .12       0  562.47    .016       0  594.61     .12       0
#XS Ineff= 2 , 0
                          431.26         1812.21
Permanent Ineff=
       F       F
Bank Sta=350.8,373.7
XS Rating Curve= 0 ,0
Exp/Cntr=0.3,0.1

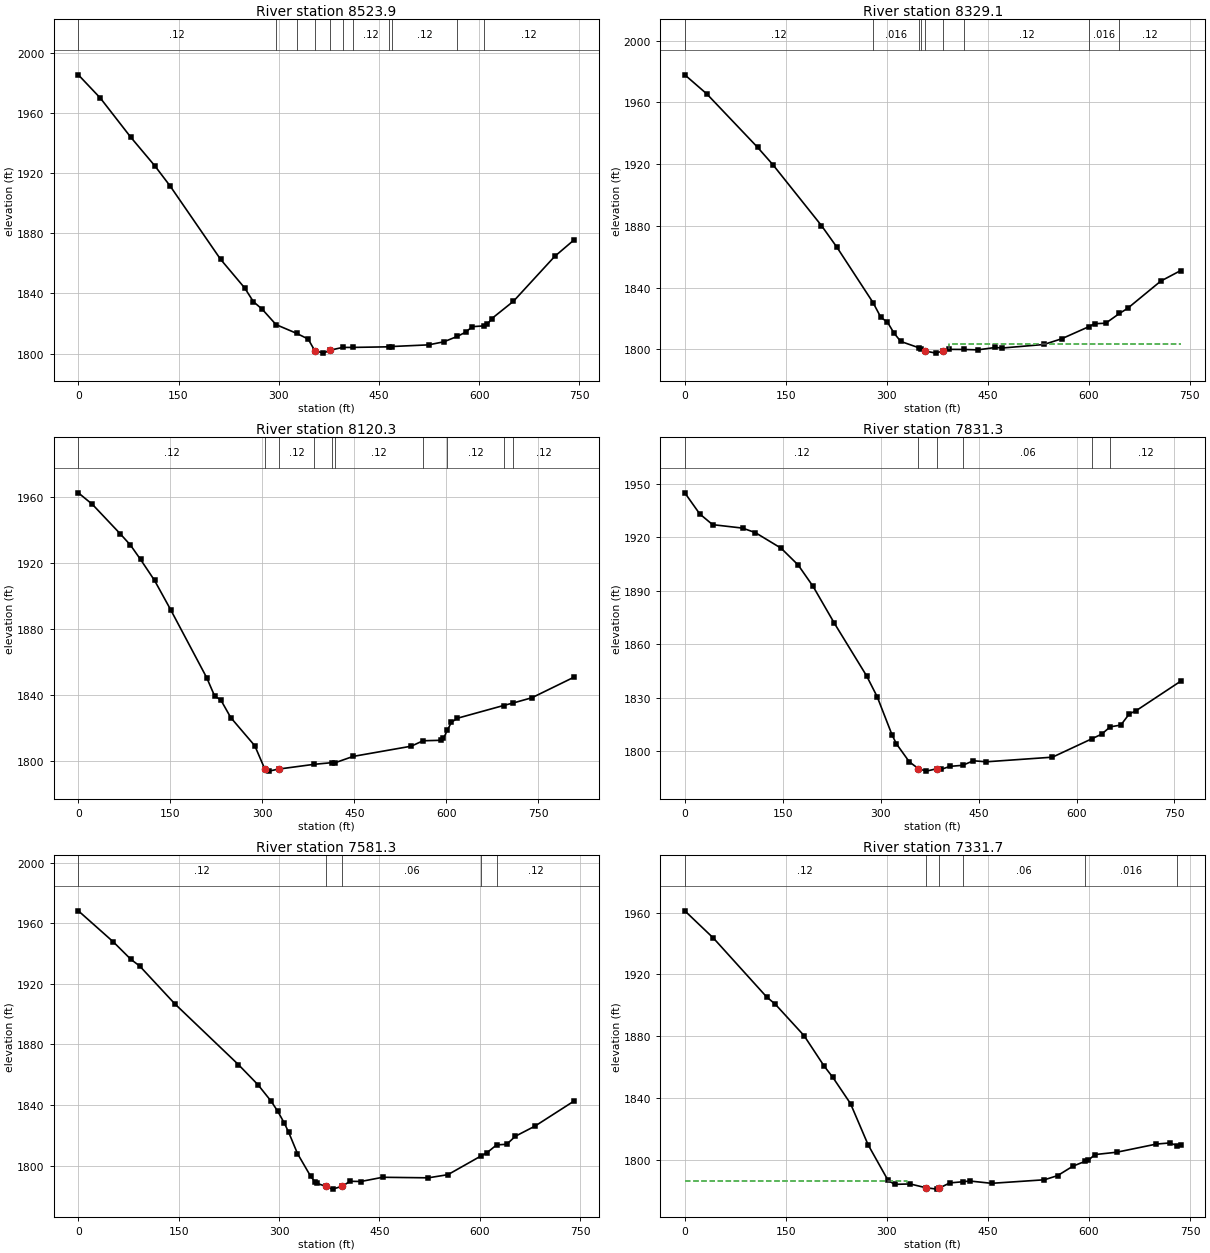
Type RM Length L Ch R = 1 ,8523.9  ,190,194.8,192.8
XS GIS Cut Line= 3
     2057916.806      176117.307     2058497.535      176237.099
     2058645.973      176221.474
#Sta/Elev= 30
       0 1985.22    32.8 1969.85    78.6 1943.72   114.7 1924.67   137.6 1911.27
   212.9 1862.71     249 1843.67   262.1 1834.54   275.2 1829.57  295.89 1819.34
  326.621813.543     344 1809.76   353.8 1802.09   366.9 1800.39   376.7 1802.31
  395.441804.175  410.831804.188  464.32 1804.58  469.25 1804.78   524.2 1805.88
   547.1  1807.9  566.911811.445   579.8 1814.29   589.7 1817.96  607.451818.507
   612.4 1819.56   618.9 1823.32   651.4 1834.86     713  1864.6   742.2 1875.65
#Mann= 11 ,-1 , 0
       0     .12       0  295.89    .016       0  326.62     .12       0
   353.8    .045       0   376.7     .12       0  395.44    .016       0
  410.83     .12       0  464.32     .04       0  469.25     .12       0
  566.91    .016       0  607.45     .12       0
Bank Sta=353.8,376.7
XS Rating Curve= 0 ,0
Exp/Cntr=0.3,0.1

Type RM Length L Ch R = 1 ,8329.1  ,209.8,208.8,210.5
XS GIS Cut Line= 3
     2057886.178      176255.696     2058235.181      176377.765
     2058596.068      176442.569
#Sta/Elev= 30
       0  1977.8    32.7 1965.43     108  1930.9   130.9 1919.57   202.9 1880.22
   225.8 1866.23  279.531830.341   291.2 1820.74     301 1817.61   310.8  1810.5
   320.7 1805.16  348.331800.944  350.241800.406   356.6 1798.98     373 1797.58
   382.8 1798.96   392.6 1800.02  415.181799.945   435.2  1799.7   461.4 1801.25
   471.2 1800.87   533.4 1803.18   559.6 1806.86  599.651814.622   608.7 1816.64
   625.1 1816.94   645.51823.255   657.8 1826.62   706.9 1844.22   736.4 1851.02
#Mann= 9 ,-1 , 0
       0     .12       0  279.53    .016       0  348.33     .12       0
  350.24    .016       0   356.6    .045       0   382.8    .016       0
  415.18     .12       0  599.65    .016       0   645.5     .12       0
#XS Ineff= 2 , 0
                          392.99          1803.5
Permanent Ineff=
       F       F
Bank Sta=356.6,382.8
XS Rating Curve= 0 ,0
Exp/Cntr=0.3,0.1

Type RM Length L Ch R = 1 ,8120.3  ,287.1,289,282.4
XS GIS Cut Line= 3
     2057841.285      176458.453     2058380.348       176606.89
      2058544.41       176794.39
#Sta/Elev= 30
       0 1962.63    22.9 1955.63    68.7 1937.58      85 1930.87   101.4 1922.18
   124.2 1909.46   150.4 1891.72   209.3 1850.35   222.3 1839.16   232.2  1836.9
   248.5 1826.13   287.7 1809.02   304.1 1794.82   310.6 1793.63     327  1794.9
   384.61797.777  413.67 1798.78   419.2  1798.8     448 1802.57   542.8 1808.78
  561.851812.063   591.9 1812.37   595.2 1813.47  601.721818.626   608.3 1823.31
   618.1 1825.76  693.131833.475  708.861835.009   739.4 1838.19   808.3 1850.73
#Mann= 10 ,-1 , 0
       0     .12       0   304.1    .045       0     327     .12       0
   384.6    .016       0  413.67     .06       0   419.2     .12       0
  561.85    .016       0  601.72     .12       0  693.13     .06       0
  708.86     .12       0
Bank Sta=304.1,327
XS Rating Curve= 0 ,0
Exp/Cntr=0.3,0.1

Type RM Length L Ch R = 1 ,7831.3  ,259.3,250,242.8
XS GIS Cut Line= 3
     2057768.151        176664.1     2058116.817      176806.409
     2058490.753      176888.403
#Sta/Elev= 30
       0 1945.01    22.9 1933.17    42.6 1927.16    88.4 1925.23   108.1 1922.68
   147.4 1913.98   173.6 1904.55   196.5 1892.52   229.2 1871.79   278.4  1842.4
   294.7 1830.63   317.6  1809.1   324.2  1804.2   343.8 1794.18  357.811790.314
     370 1788.94   386.4 1790.32     393 1789.95     406 1791.61   425.51792.198
     442 1794.75   461.7 1794.17   563.1 1796.77  623.761807.131   638.4 1809.66
  651.571813.781   667.8 1814.76   680.9 1821.09   690.7  1822.7   759.4 1839.35
#Mann= 6 ,-1 , 0
       0     .12       0  357.81    .045       0   386.4     .12       0
   425.5     .06       0  623.76    .016       0  651.57     .12       0
Bank Sta=357.81,386.4
XS Rating Curve= 0 ,0
Exp/Cntr=0.3,0.1

Type RM Length L Ch R = 1 ,7581.3  ,239.1,249.6,263.9
XS GIS Cut Line= 3
     2057762.783      177071.622     2058140.252      177027.467
     2058494.729      176958.274
#Sta/Elev= 30
       0 1968.19    52.4 1947.65    78.6 1936.15    91.7 1931.77   144.2 1906.84
   239.2 1866.76   268.6 1853.41   288.3 1842.52   298.1  1835.9     308 1828.06
   314.5 1821.99   327.6 1808.02   347.3 1793.02   353.8 1789.35   357.1 1788.31
   370.2 1786.37     380 1784.55  394.831786.483   406.1 1789.73   422.3 1789.58
   454.9 1792.37   523.2 1792.01   552.5 1794.09  602.151806.483   611.1 1808.66
  625.321813.753   640.3 1814.13   653.4 1819.46   682.6 1826.12   741.2 1842.72
#Mann= 5 ,-1 , 0
       0     .12       0   370.2    .045       0  394.83     .06       0
  602.15    .016       0  625.32     .12       0
Bank Sta=370.2,394.83
XS Rating Curve= 0 ,0
Exp/Cntr=0.3,0.1

Type RM Length L Ch R = 1 ,7331.7  ,238.4,249,246.4
XS GIS Cut Line= 3
     2057753.449      177143.492     2058105.278      177270.115
     2058424.711      177440.856
#Sta/Elev= 30
       0  1961.1    42.6 1943.44   121.4 1905.54   134.5 1900.72   177.1 1880.48
   206.6 1861.01   219.8 1853.54     246 1836.63   272.2 1809.97   301.8 1786.99
   311.6 1784.47   334.6 1784.73   357.5 1782.33   373.9 1781.39   377.2 1781.96
   393.5 1785.41  413.351786.167   422.9 1786.64   455.5 1785.14   533.8 1787.42
   553.4  1790.1   576.2 1796.22  593.751799.251   599.1 1800.06   608.9  1803.7
   641.5 1805.24   700.2 1810.49   719.8 1811.21  731.391809.457   736.1 1809.71
#Mann= 6 ,-1 , 0
       0     .12       0   357.5    .045       0   377.2     .12       0
  413.35     .06       0  593.75    .016       0  731.39     .12       0
#XS Ineff= 2 , 0
          329.41 1786.72
Permanent Ineff=
       F       F
Bank Sta=357.5,377.2
XS Rating Curve= 0 ,0
Exp/Cntr=0.3,0.1

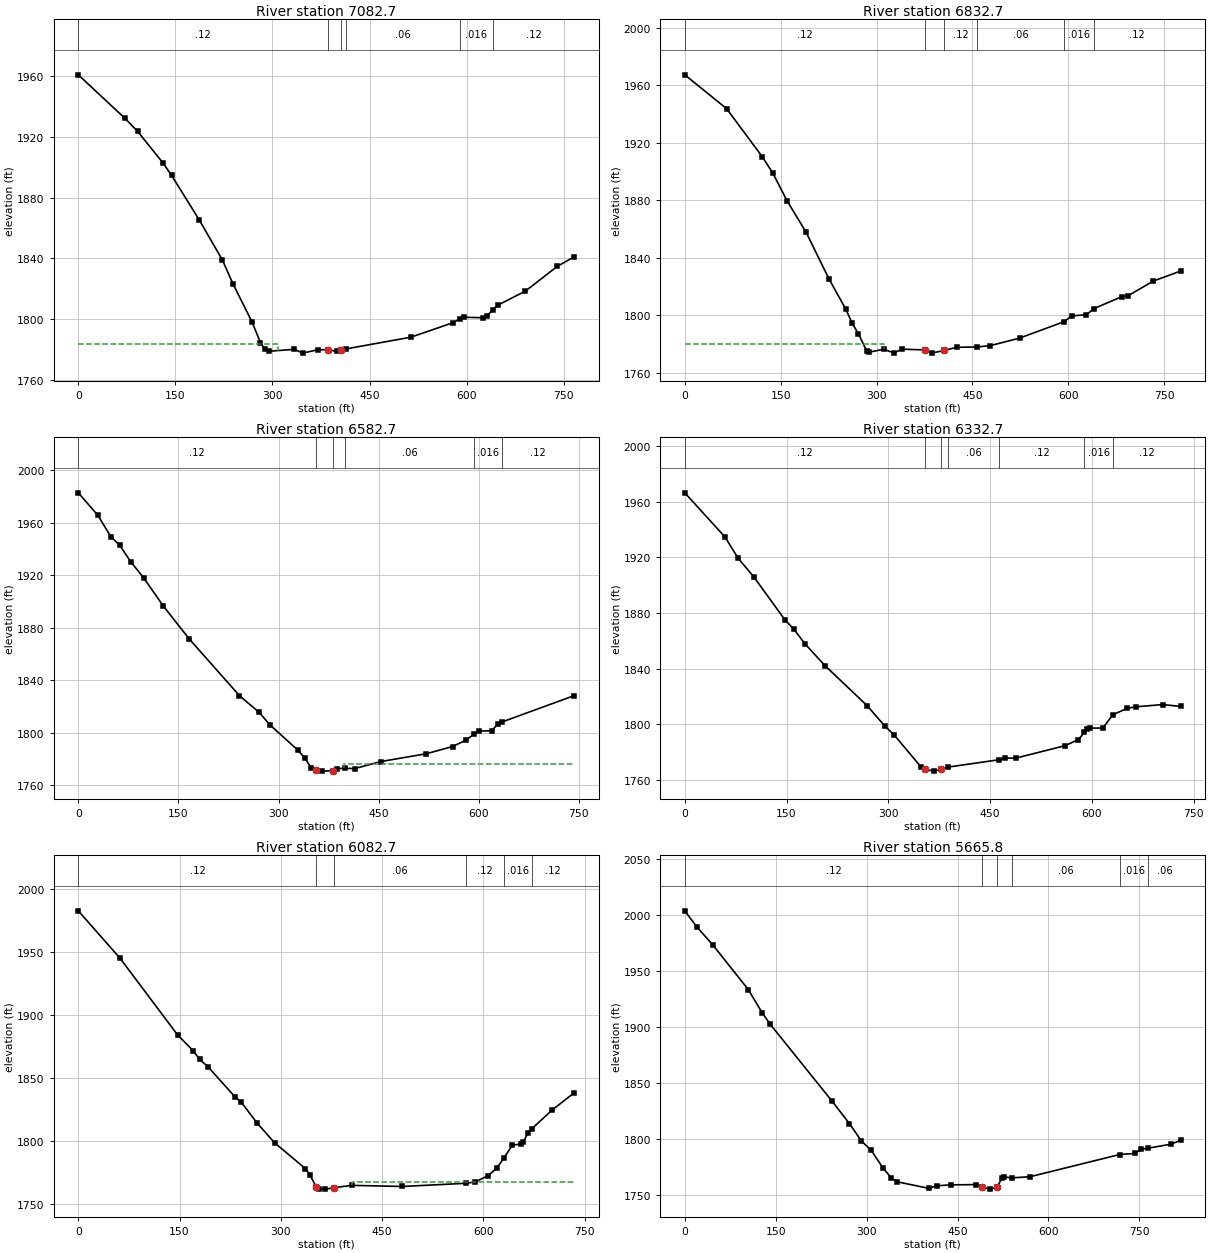
Type RM Length L Ch R = 1 ,7082.7  ,242.1,250,273.3
XS GIS Cut Line= 3
     2057719.226       177209.78     2058000.305      177493.173
     2058345.418      177617.971
#Sta/Elev= 30
       0 1960.85      72  1932.2    91.6 1923.63   130.9 1902.78     144 1894.67
   186.5 1865.57   222.5    1839   238.8 1823.37   268.3 1798.23   281.4 1784.63
   287.9 1780.34   294.4 1778.88   333.7 1780.14   346.8 1777.64   369.7 1779.86
   386.1 1779.87   399.1 1778.75   405.7 1779.87   413.81780.427   513.8 1788.14
   579.4 1797.74  589.251800.252   595.7 1801.27   625.2 1800.95   631.8 1802.28
  640.611806.346   648.2 1809.24   690.8 1818.48   739.9 1834.71   766.1 1841.06
#Mann= 6 ,-1 , 0
       0     .12       0   386.1    .045       0   405.7     .12       0
   413.8     .06       0  589.25    .016       0  640.61     .12       0
#XS Ineff= 2 , 0
          308.04 1783.91
Permanent Ineff=
       F       F
Bank Sta=386.1,405.7
XS Rating Curve= 0 ,0
Exp/Cntr=0.3,0.1

Type RM Length L Ch R = 1 ,6832.7  ,258.7,250,238.9
XS GIS Cut Line= 3
     2057678.392      177241.685     2057852.105      177586.593
     2057921.118      177969.999
#Sta/Elev= 30
       0 1967.33    65.4 1943.78   121.1 1910.42   137.5 1899.08   160.4 1879.34
   189.8 1857.79   225.8 1825.14     252 1804.18   261.8 1794.53   271.6 1787.12
   284.7 1775.13     288  1774.3   310.9 1776.33   327.3 1773.84   340.4 1776.42
   376.4 1775.85   386.2 1773.66   405.8 1775.52   425.5 1777.72   457.11777.923
   477.8 1778.87   523.7 1784.08  593.311795.523   605.5 1799.56   628.4  1800.4
  640.241804.676   684.1    1813   693.9 1813.66   733.2 1823.85   775.8 1830.78
#Mann= 6 ,-1 , 0
       0     .12       0   376.4    .045       0   405.8     .12       0
   457.1     .06       0  593.31    .016       0  640.24     .12       0
#XS Ineff= 2 , 0
          311.67 1780.01
Permanent Ineff=
       F       F
Bank Sta=376.4,405.8
XS Rating Curve= 0 ,0
Exp/Cntr=0.3,0.1

Type RM Length L Ch R = 1 ,6582.7  ,250.2,250,242.7
XS GIS Cut Line= 3
     2057373.165      177451.898     2057653.121      177686.716
     2057862.348      178001.062
#Sta/Elev= 30
       0 1982.76    29.4 1965.54    48.9 1949.17      62 1942.87    78.3 1930.37
    97.9 1917.98   127.2 1896.58   166.4 1871.27   241.4 1828.21   270.8 1815.55
   287.1 1805.92   329.5  1786.4   339.3 1780.68   349.1  1773.1   355.6 1771.37
   365.4 1770.67   381.7    1771   388.2 1772.61  398.881772.795   414.2  1772.6
   453.3 1777.97   521.6 1783.92   560.7 1789.42   580.2 1794.07  593.621799.127
   599.8 1801.19   619.3 1801.43   629.1 1806.84   634.91808.137     743  1828.2
#Mann= 6 ,-1 , 0
       0     .12       0   355.6    .045       0   381.7     .12       0
  398.88     .06       0  593.62    .016       0   634.9     .12       0
#XS Ineff= 2 , 0
                          398.78         1776.18
Permanent Ineff=
       F       F
Bank Sta=355.6,381.7
XS Rating Curve= 0 ,0
Exp/Cntr=0.3,0.1

Type RM Length L Ch R = 1 ,6332.7  ,244.1,250,254.4
XS GIS Cut Line= 3
     2057188.947      177635.549      2057479.26      177860.674
     2057758.099      178093.941
#Sta/Elev= 30
       0 1966.58      59 1934.91    78.7 1919.42   101.7 1906.04   147.6 1875.06
   160.7 1868.37   177.1 1857.81   206.6  1842.1     269 1813.11   295.2 1798.32
   308.3 1792.35   347.7 1769.36   354.2 1767.27   367.4 1766.07   377.2 1767.35
  387.971768.973  463.841774.305   472.2 1775.39   488.6 1775.51   560.6 1784.42
   580.3 1788.83  589.011793.927   593.4 1796.46   596.6 1797.07   616.3  1797.1
  631.05 1806.73   652.3 1811.35   665.4 1812.44   704.7 1814.03   730.9 1812.66
#Mann= 7 ,-1 , 0
       0     .12       0   354.2    .045       0   377.2     .12       0
  387.97     .06       0  463.84     .12       0  589.01    .016       0
  631.05     .12       0
Bank Sta=354.2,377.2
XS Rating Curve= 0 ,0
Exp/Cntr=0.3,0.1

Type RM Length L Ch R = 1 ,6082.7  ,406.7,416.9,421.8
XS GIS Cut Line= 3
     2057068.883      177741.737     2057297.666      178023.047
     2057523.011      178319.007
#Sta/Elev= 30
       0 1982.59    62.1 1944.82     147 1884.29   169.9 1871.86   179.7 1864.94
   192.7 1858.65   231.9 1835.29   241.7 1830.79   264.6  1814.6   290.7 1798.82
   336.5 1778.29     343 1773.38   352.8 1763.49   356.1 1762.28   365.9 1762.07
   378.9  1763.2     405 1765.05   480.1 1764.17  573.751766.677   587.8 1767.72
   607.3 1772.82   620.4 1779.01  630.581786.737   643.2    1797   656.3 1797.75
   659.5 1799.61   666.1 1806.64  671.751809.825     702 1824.78   734.6 1838.36
#Mann= 6 ,-1 , 0
       0     .12       0   352.8    .045       0   378.9     .06       0
  573.75     .12       0  630.58    .016       0  671.75     .12       0
#XS Ineff= 2 , 0
                          405.09         1767.96
Permanent Ineff=
       F       F
Bank Sta=352.8,378.9
XS Rating Curve= 0 ,0
Exp/Cntr=0.3,0.1

Type RM Length L Ch R = 1 ,5665.8  ,331.4,333.1,341
XS GIS Cut Line= 3
     2056901.181      177849.078     2057091.285      178427.203
     2057221.493      178591.265
#Sta/Elev= 30
       0 2003.37    19.6 1989.16    45.8 1973.22   104.7 1933.11   127.6 1912.39
   140.7 1902.23   242.1 1834.01   271.6 1813.47   291.2 1797.99   307.6 1789.46
   327.2 1773.65   340.3 1765.15   350.1 1761.45   402.4 1755.61   415.5 1757.86
   438.4  1758.7     481 1758.94   490.8  1756.8   503.9 1754.89  515.04 1756.81
   523.5  1764.7   526.8 1765.75  539.961764.957   569.3 1765.94  717.481785.799
   742.8 1786.73   752.6 1790.51  764.971791.497   801.7 1794.97     818 1798.46
#Mann= 6 ,-1 , 0
       0     .12       0   490.8    .045       0  515.04     .12       0
  539.96     .06       0  717.48    .016       0  764.97     .06       0
Bank Sta=490.8,515.04
XS Rating Curve= 0 ,0
Exp/Cntr=0.3,0.1