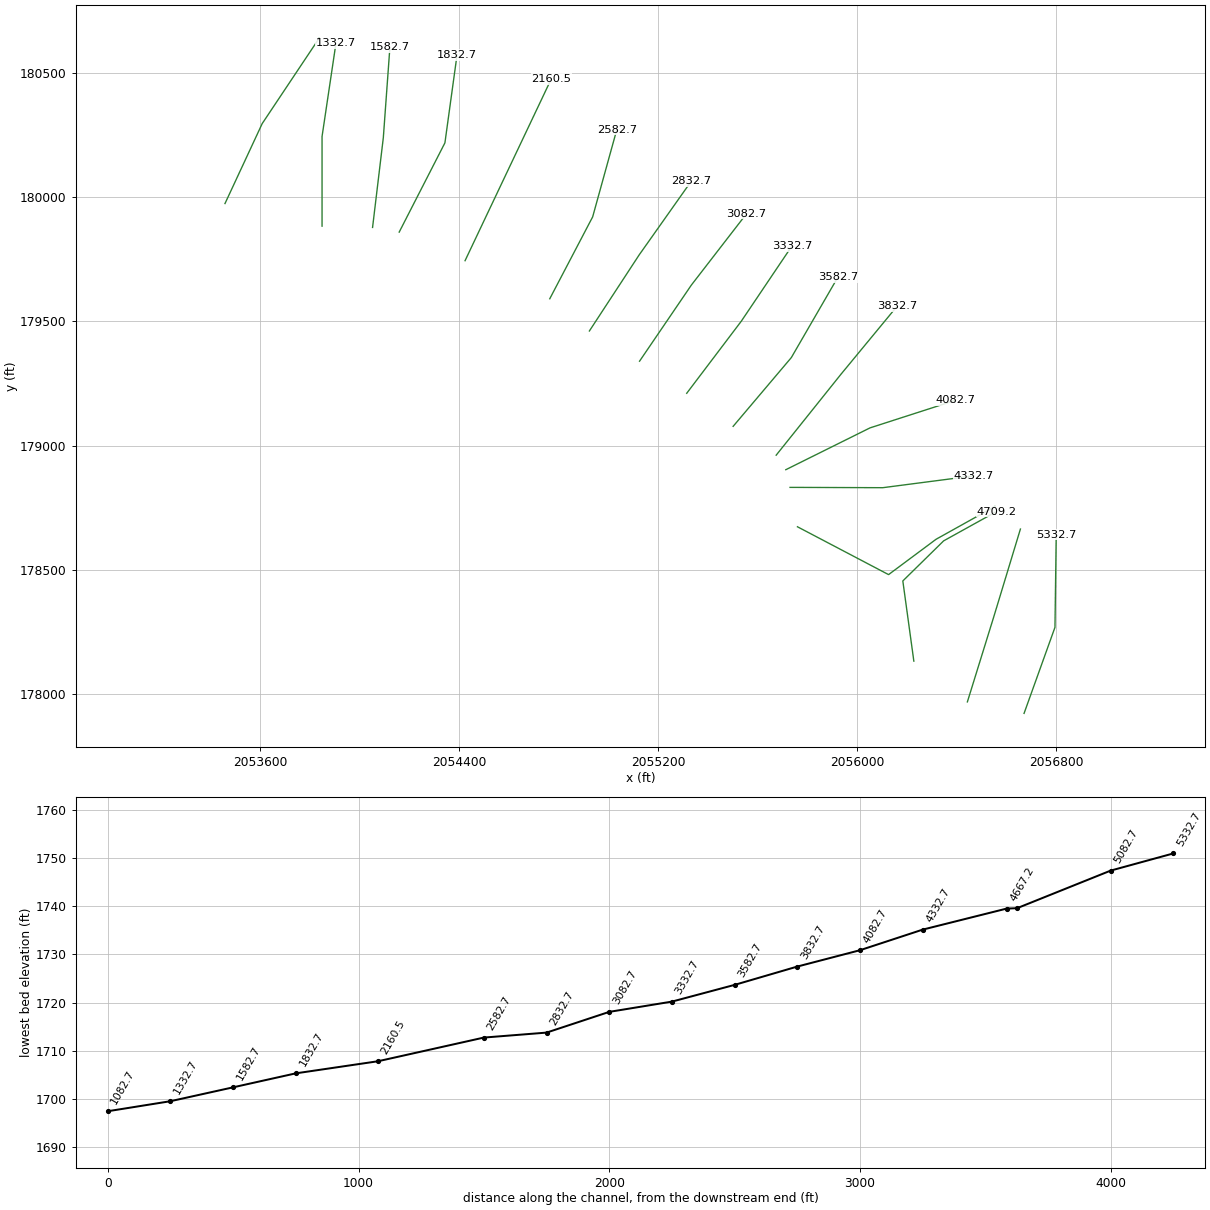
HEC-RAS study BLLKCK.prj: BLLKCK

--- BLLKCK.g01 (geometry) --- (continued)

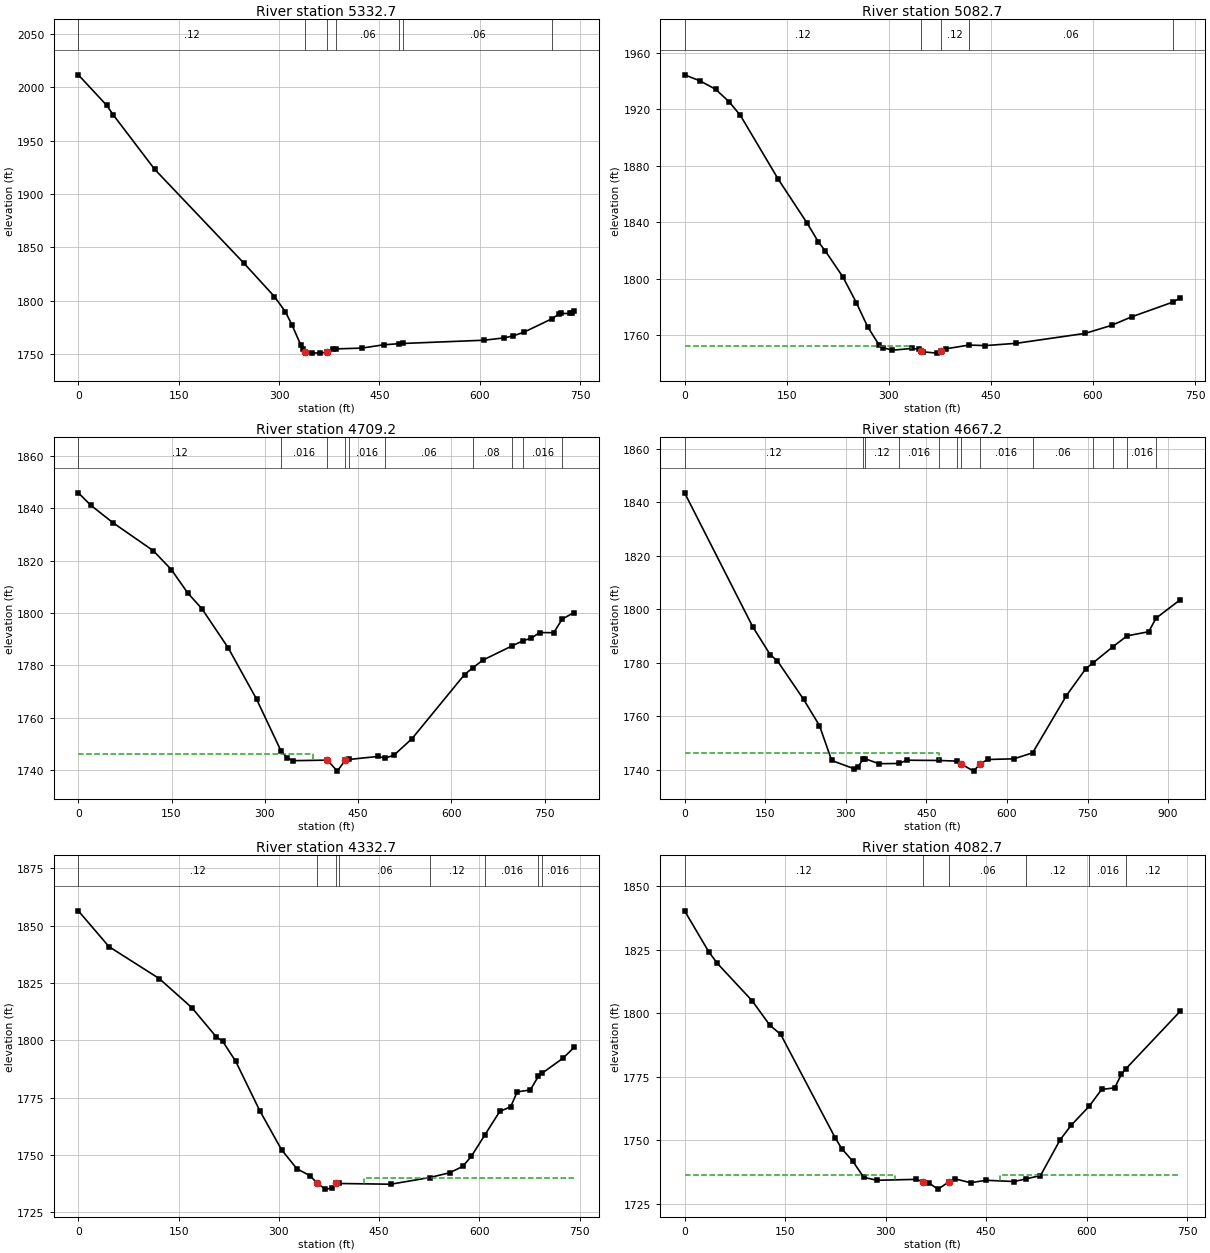
Type RM Length L Ch R = 1 ,5332.7  ,248.9,250,243.2
XS GIS Cut Line= 3
     2056671.459      177921.576     2056795.673      178268.112
     2056800.686      178640.714
#Sta/Elev= 30
       0 2011.54    42.4 1982.96    52.1 1974.15     114 1923.14   247.6 1835.09
   293.2 1803.81   309.5 1789.67   319.3 1777.36   332.3 1758.79   335.6 1754.94
   338.8 1752.44   348.6 1751.23   361.6 1750.93   371.4 1751.84   381.2 1754.45
  385.721754.902   423.7 1755.63   456.4 1758.75  479.511759.757  485.861759.992
   606.7 1763.02   636.2 1765.19   649.2 1766.97   665.6  1770.4  708.231783.226
   717.9 1787.39   721.2 1788.08   734.2 1788.06   737.5 1788.58   740.8 1790.48
#Mann= 7 ,-1 , 0
       0     .12       0   338.8    .045       0   371.4     .12       0
  385.72     .06       0  479.51     .12       0  485.86     .06       0
  708.23    .016       0
Bank Sta=338.8,371.4
XS Rating Curve= 0 ,0
Exp/Cntr=0.3,0.1

Type RM Length L Ch R = 1 ,5082.7  ,384.4,373.5,361.8
XS GIS Cut Line= 3
     2056443.605      177967.768     2056551.218      178315.453
     2056656.777      178664.057
#Sta/Elev= 30
       0 1944.22      23 1939.88    45.9 1933.89    65.6 1925.07      82  1915.5
   137.7 1870.29   180.3 1839.11   196.7  1825.9   206.6 1819.73   232.8 1801.11
   252.5 1782.87   268.9 1766.07   285.3 1753.46   291.8 1751.24   304.9 1749.42
   334.4 1750.69   344.3 1750.19   347.6 1749.22   350.8 1748.27   370.5 1747.37
     377 1748.59   383.5  1750.4  417.861753.071     442  1752.7   487.5 1754.33
   588.4 1761.32   627.4 1767.03   656.6    1773  718.251783.625   728.2  1786.5
#Mann= 5 ,-1 , 0
       0     .12       0   347.6    .045       0     377     .12       0
  417.86     .06       0  718.25    .016       0
#XS Ineff= 2 , 0
          332.91 1752.76
Permanent Ineff=
       F       F
Bank Sta=347.6,377
XS Rating Curve= 0 ,0
Exp/Cntr=0.3,0.1

Type RM Length L Ch R = 1 ,4709.2  ,45.1,42,39
XS GIS Cut Line= 4
     2056228.438      178132.064     2056184.167       178454.98
      2056348.23      178616.439     2056559.167      178733.626
#Sta/Elev= 30
       0 1845.92    19.6 1841.27    55.4 1834.55   120.6  1823.8   149.9 1816.51
     176 1807.64   198.8 1801.64   241.2 1786.65   286.8 1767.05  326.081747.274
   335.7  1744.7   345.4 1743.56   400.5 1743.77   416.7 1739.57   429.7 1743.83
  435.511744.034   481.6 1745.16  493.421744.574   507.5 1745.61   536.7 1751.94
   621.3 1776.46  634.271778.982   650.7 1781.97  697.661787.408  715.421789.391
     729 1790.38     742 1792.53   764.8 1792.46  778.411797.653   797.4 1800.17
#Mann= 10 ,-1 , 0
       0     .12       0  326.08    .016       0   400.5    .045       0
   429.7     .12       0  435.51    .016       0  493.42     .06       0
  634.27     .08       0  697.66     .06       0  715.42    .016       0
  778.41     .12       0
#XS Ineff= 2 , 0
          377.12 1745.95
Permanent Ineff=
       F       F
Bank Sta=400.5,429.7
XS Rating Curve= 0 ,0
Exp/Cntr=0.3,0.1

Type RM Length L Ch R = 1 ,4667.2  ,348.9,334.6,320.7
XS GIS Cut Line= 4
     2055760.556       178673.21     2056126.875      178480.501
     2056317.848      178622.862     2056553.959      178754.807
#Sta/Elev= 30
       0 1843.51   127.1 1793.34   159.7 1782.91   172.7 1780.71   221.6 1766.27
     251 1756.51   273.8 1743.46   316.1 1740.32   322.7 1740.94  331.711743.855
   336.51744.066   361.8 1742.26  399.131742.337   413.9 1743.56  474.23 1743.46
  507.391743.217   515.1 1742.12   537.9 1739.48  549.621742.071     564 1743.83
     613 1744.08  647.851746.325   710.8 1767.73   746.6 1777.72  760.261779.944
  797.521786.026  823.731790.053   863.9 1791.59  877.431796.626   922.6 1803.56
#Mann= 13 ,-1 , 0
       0     .12       0  331.71     .06       0   336.5     .12       0
  399.13    .016       0  474.23     .06       0  507.39    .016       0
   515.1    .045       0  549.62    .016       0  647.85     .06       0
  760.26     .08       0  797.52     .06       0  823.73    .016       0
  877.43     .12       0
#XS Ineff= 2 , 0
          472.89 1746.22
Permanent Ineff=
       F       F
Bank Sta=515.1,549.62
XS Rating Curve= 0 ,0
Exp/Cntr=0.3,0.1

Type RM Length L Ch R = 1 ,4332.7  ,239.3,250,254
XS GIS Cut Line= 3
     2055730.802      178831.857     2056103.463      178830.587
     2056469.076      178878.236
#Sta/Elev= 30
       0 1856.47    45.8 1840.86     121 1826.94     170 1814.19     206 1801.62
   215.8 1799.64   235.4 1790.85   271.3 1769.38     304 1752.29   326.9 1744.01
   346.5    1741  357.351737.687   369.4 1735.12   379.2 1735.52   385.7 1737.61
  390.521737.578   467.3 1737.26  525.321740.157   555.4 1742.25     575 1745.02
     588 1749.48  608.291758.831   630.4 1769.01   646.7 1771.02   656.5 1777.52
   676.1 1778.37  688.191784.337  693.091785.539     725 1792.21   741.4 1796.88
#Mann= 8 ,-1 , 0
       0     .12       0  357.35    .045       0   385.7     .12       0
  390.52     .06       0  525.32     .12       0  608.29    .016       0
  688.19     .12       0  693.09    .016       0
#XS Ineff= 2 , 0
                           427.5         1740.11
Permanent Ineff=
       F       F
Bank Sta=357.35,385.7
XS Rating Curve= 0 ,0
Exp/Cntr=0.3,0.1

Type RM Length L Ch R = 1 ,4082.7  ,239.8,250,262.6
XS GIS Cut Line= 3
     2055713.798      178903.016     2056052.124      179071.435
     2056396.186      179182.595
#Sta/Elev= 30
       0 1840.26    35.8 1824.26    48.9 1819.58     101 1804.83   127.1 1795.31
   143.4 1791.67   224.8 1750.96   234.6 1746.73   250.9 1741.82   267.2 1735.52
   286.7 1734.32   345.4 1734.69   355.1  1733.8   364.9  1733.2   377.9 1730.85
   394.2 1733.63     404 1734.85   426.8 1733.36   449.6 1734.33   491.9 1733.84
  510.041734.916     531 1736.18   560.3 1750.25   576.6 1755.89  603.941763.529
   622.2 1770.04   641.8 1770.67   651.6 1775.98  658.691778.242   739.5 1800.79
#Mann= 6 ,-1 , 0
       0     .12       0   355.1    .045       0   394.2     .06       0
  510.04     .12       0  603.94    .016       0  658.69     .12       0
#XS Ineff= 2 , 0
          313.53 1736.26  470.67         1736.26
Permanent Ineff=
       F       F
Bank Sta=355.1,394.2
XS Rating Curve= 0 ,0
Exp/Cntr=0.3,0.1

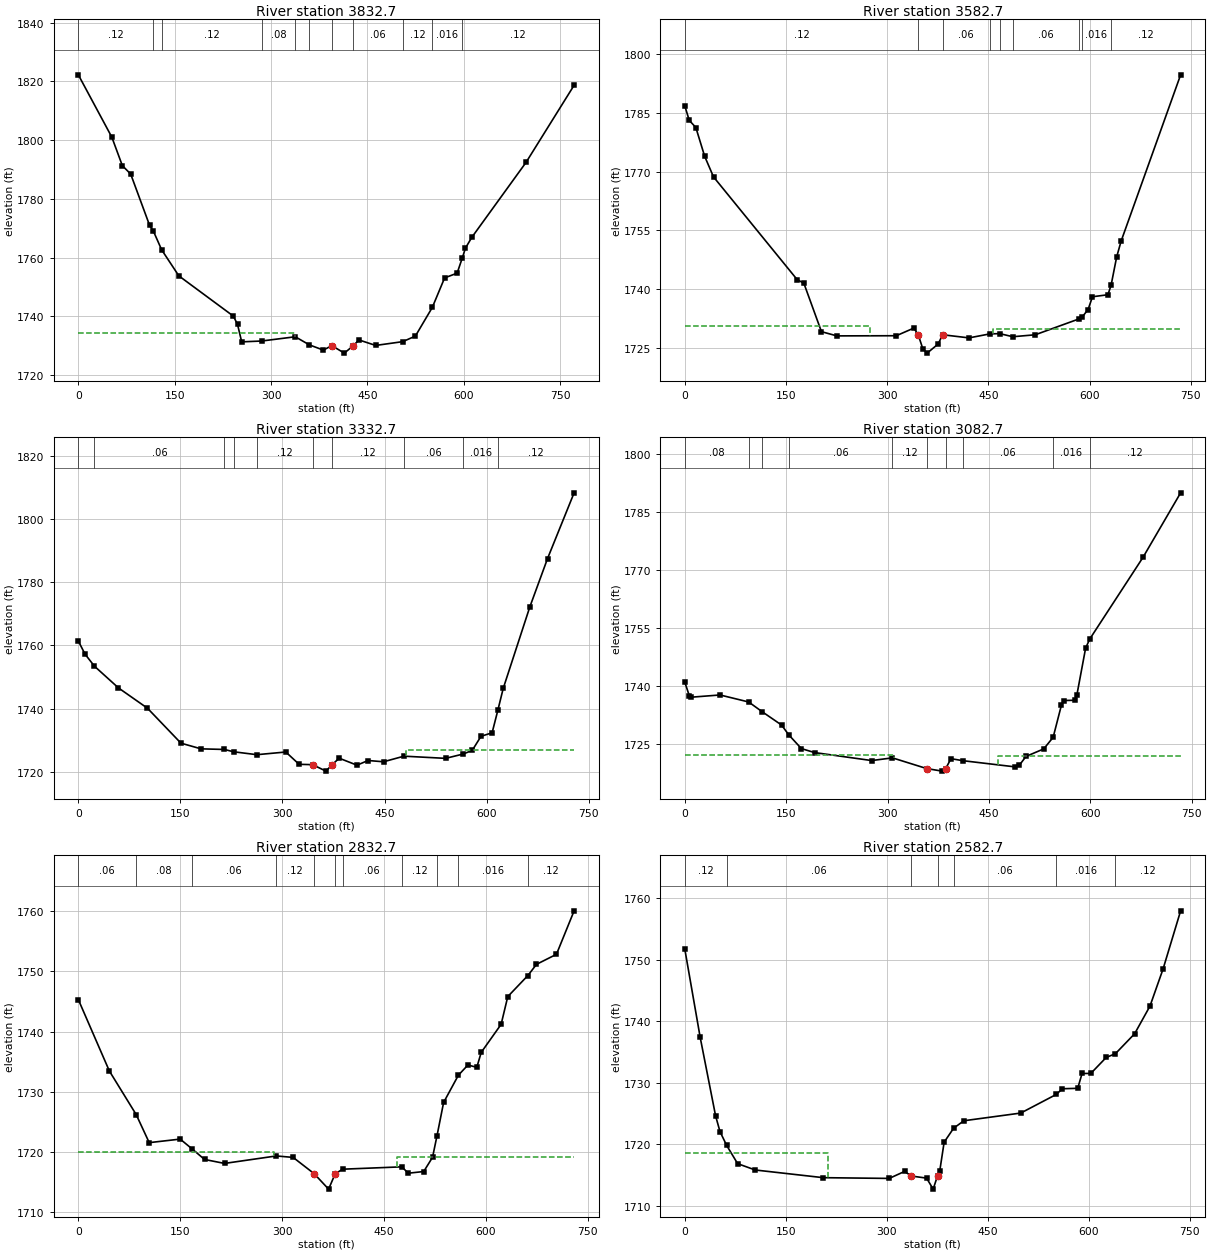
Type RM Length L Ch R = 1 ,3832.7  ,245,250,259.7
XS GIS Cut Line= 3
     2055675.167      178961.609     2055935.681      179287.694
     2056160.987      179561.285
#Sta/Elev= 30
       0 1822.24    52.2 1800.99    68.5 1791.32    81.5 1788.45   110.9    1771
  116.721769.068  129.691762.655   156.5 1753.77   241.3 1740.07   247.8 1737.27
   254.3  1731.3  285.15 1731.58  337.73 1733.03  359.711730.268   381.5 1728.49
   394.6 1730.02   414.1 1727.46  428.161730.022   436.9 1731.95   462.9 1730.08
  504.941731.367   524.7 1733.26  551.121743.056   570.2 1753.08   589.7  1754.7
  597.741759.881   602.7 1763.24   612.5 1766.88     697 1792.43   771.8 1818.69
#Mann= 11 ,-1 , 0
       0     .12       0  116.72     .06       0  129.69     .12       0
  285.15     .08       0  337.73     .06       0  359.71     .12       0
   394.6    .045       0  428.16     .06       0  504.94     .12       0
  551.12    .016       0  597.74     .12       0
#XS Ineff= 2 , 0
          337.82 1734.19
Permanent Ineff=
       F       F
Bank Sta=394.6,428.16
XS Rating Curve= 0 ,0
Exp/Cntr=0.3,0.1

Type RM Length L Ch R = 1 ,3582.7  ,248.6,250,248.2
XS GIS Cut Line= 3
      2055502.16      179077.723     2055736.045      179354.691
     2055922.391      179677.226
#Sta/Elev= 30
       0 1786.72     6.5 1783.08    16.3 1781.24    29.4 1773.88    42.5 1768.64
   166.6  1742.4   176.4 1741.52   202.5 1729.14   225.3 1728.06   313.5  1728.1
   339.6 1730.06   346.2 1728.23   352.7 1724.81   359.2 1723.66   375.6    1726
   382.1 1728.35   421.3 1727.55  452.071728.566  466.821728.636  486.181727.847
   519.4 1728.34   584.91732.426  588.531732.764   597.8 1734.79   604.3 1738.05
   627.2 1738.56  631.891740.976   640.2 1748.23   646.8 1752.26     735 1794.69
#Mann= 9 ,-1 , 0
       0     .12       0   346.2    .045       0   382.1     .06       0
  452.07     .08       0  466.82     .12       0  486.18     .06       0
   584.9     .12       0  588.53    .016       0  631.89     .12       0
#XS Ineff= 2 , 0
          274.31 1730.49  457.52         1729.83
Permanent Ineff=
       F       F
Bank Sta=346.2,382.1
XS Rating Curve= 0 ,0
Exp/Cntr=0.3,0.1

Type RM Length L Ch R = 1 ,3332.7  ,248.8,250,248.5
XS GIS Cut Line= 3
     2055315.613      179210.925     2055534.973      179501.253
     2055738.371      179803.941
#Sta/Elev= 30
       0 1761.35     9.8 1757.22   23.641753.392      59 1746.51   101.6 1740.09
   150.8 1729.04   180.3 1727.24   214.81727.043  228.071726.314  262.381725.392
   304.9 1726.24   324.5 1722.34   344.2 1722.24   363.9 1720.19  372.551722.155
   383.4 1724.28   409.5 1722.07   425.8 1723.55   448.5 1723.15   478.61724.922
   539.7 1724.23  565.431725.589   578.8 1726.73   591.8 1731.21   608.1 1732.32
  616.641739.549   624.4 1746.34   663.4 1772.06   689.5 1787.41   728.6 1808.23
#Mann= 10 ,-1 , 0
       0     .12       0   23.64     .06       0   214.8     .08       0
  228.07     .06       0  262.38     .12       0   344.2    .045       0
  372.55     .12       0   478.6     .06       0  565.43    .016       0
  616.64     .12       0
#XS Ineff= 2 , 0
                          481.99         1726.75
Permanent Ineff=
       F       F
Bank Sta=344.2,372.55
XS Rating Curve= 0 ,0
Exp/Cntr=0.3,0.1

Type RM Length L Ch R = 1 ,3082.7  ,249.1,250,250.1
XS GIS Cut Line= 3
     2055125.976      179340.107     2055334.448      179647.006
     2055556.026      179934.235
#Sta/Elev= 30
       0 1740.99     6.5 1737.59     9.8 1737.16    52.1 1737.73   94.491735.917
  114.091733.446   143.2 1729.96   153.81727.427   172.5 1723.88     192 1722.85
   276.6 1720.79  307.241721.487     358 1718.72   380.8 1718.06  385.981718.684
   393.9 1721.28  411.251720.763   488.7 1719.16   495.2 1719.62     505 1721.86
   531.2  1723.8  545.13  1726.8   557.3 1735.06   560.6  1736.3   576.9 1736.36
   580.2 1737.69   593.2 1749.85  599.411752.204   678.2  1773.3   733.8 1789.94
#Mann= 10 ,-1 , 0
       0     .08       0   94.49     .06       0  114.09     .08       0
   153.8     .06       0  307.24     .12       0     358    .045       0
  385.98     .12       0  411.25     .06       0  545.13    .016       0
  599.41     .12       0
#XS Ineff= 2 , 0
          309.84 1722.34  463.94         1721.93
Permanent Ineff=
       F       F
Bank Sta=358,385.98
XS Rating Curve= 0 ,0
Exp/Cntr=0.3,0.1

Type RM Length L Ch R = 1 ,2832.7  ,247.4,250,257.6
XS GIS Cut Line= 3
     2054924.326       179461.74     2055124.036      179767.618
     2055334.367      180065.856
#Sta/Elev= 30
       0 1745.32    45.7 1733.43   85.271726.162   104.4  1721.5     150 1722.09
  167.791720.436   185.9  1718.7   215.3 1718.04  291.681719.286   316.4 1719.04
  347.311716.333   368.6 1713.76   378.3 1716.31  389.281717.079   476.51717.472
   485.9 1716.41   508.7 1716.69   521.7 1719.06  528.291722.656     538 1728.19
  559.791732.731   573.8 1734.43   586.9 1734.04   593.4 1736.53   622.7  1741.2
   632.5 1745.82  662.091749.322   674.8 1751.19   704.2 1752.86   730.2  1760.1
#Mann= 11 ,-1 , 0
       0     .06       0   85.27     .08       0  167.79     .06       0
  291.68     .12       0  347.31    .045       0   378.3     .12       0
  389.28     .06       0   476.5     .12       0  528.29     .06       0
  559.79    .016       0  662.09     .12       0
#XS Ineff= 2 , 0
          288.61 1719.97  469.25          1719.1
Permanent Ineff=
       F       F
Bank Sta=347.31,378.3
XS Rating Curve= 0 ,0
Exp/Cntr=0.3,0.1

Type RM Length L Ch R = 1 ,2582.7  ,420,422.1,417.6
XS GIS Cut Line= 3
     2054765.072      179591.566     2054937.507      179921.382
     2055034.478      180272.583
#Sta/Elev= 30
       0 1751.68    22.8 1737.38    45.7 1724.62    52.2 1722.08   62.131719.828
    78.4 1716.87   104.5 1715.84   205.7 1714.59   303.6 1714.47   326.5 1715.61
   336.3 1714.86   359.1 1714.52   368.9 1712.73   375.4  1714.9   378.7 1715.71
   385.2 1720.36  399.251722.626   414.5 1723.84     499 1725.09  551.781728.117
   560.8 1729.04   583.6 1729.11   590.1 1731.52   603.1 1731.53   625.9 1734.12
  639.66 1734.74   668.2 1737.98     691 1742.48   710.5 1748.53   736.5 1757.95
#Mann= 7 ,-1 , 0
       0     .12       0   62.13     .06       0   336.3    .045       0
   375.4     .12       0  399.25     .06       0  551.78    .016       0
  639.66     .12       0
#XS Ineff= 2 , 0
          212.18 1718.53
Permanent Ineff=
       F       F
Bank Sta=336.3,375.4
XS Rating Curve= 0 ,0
Exp/Cntr=0.3,0.1

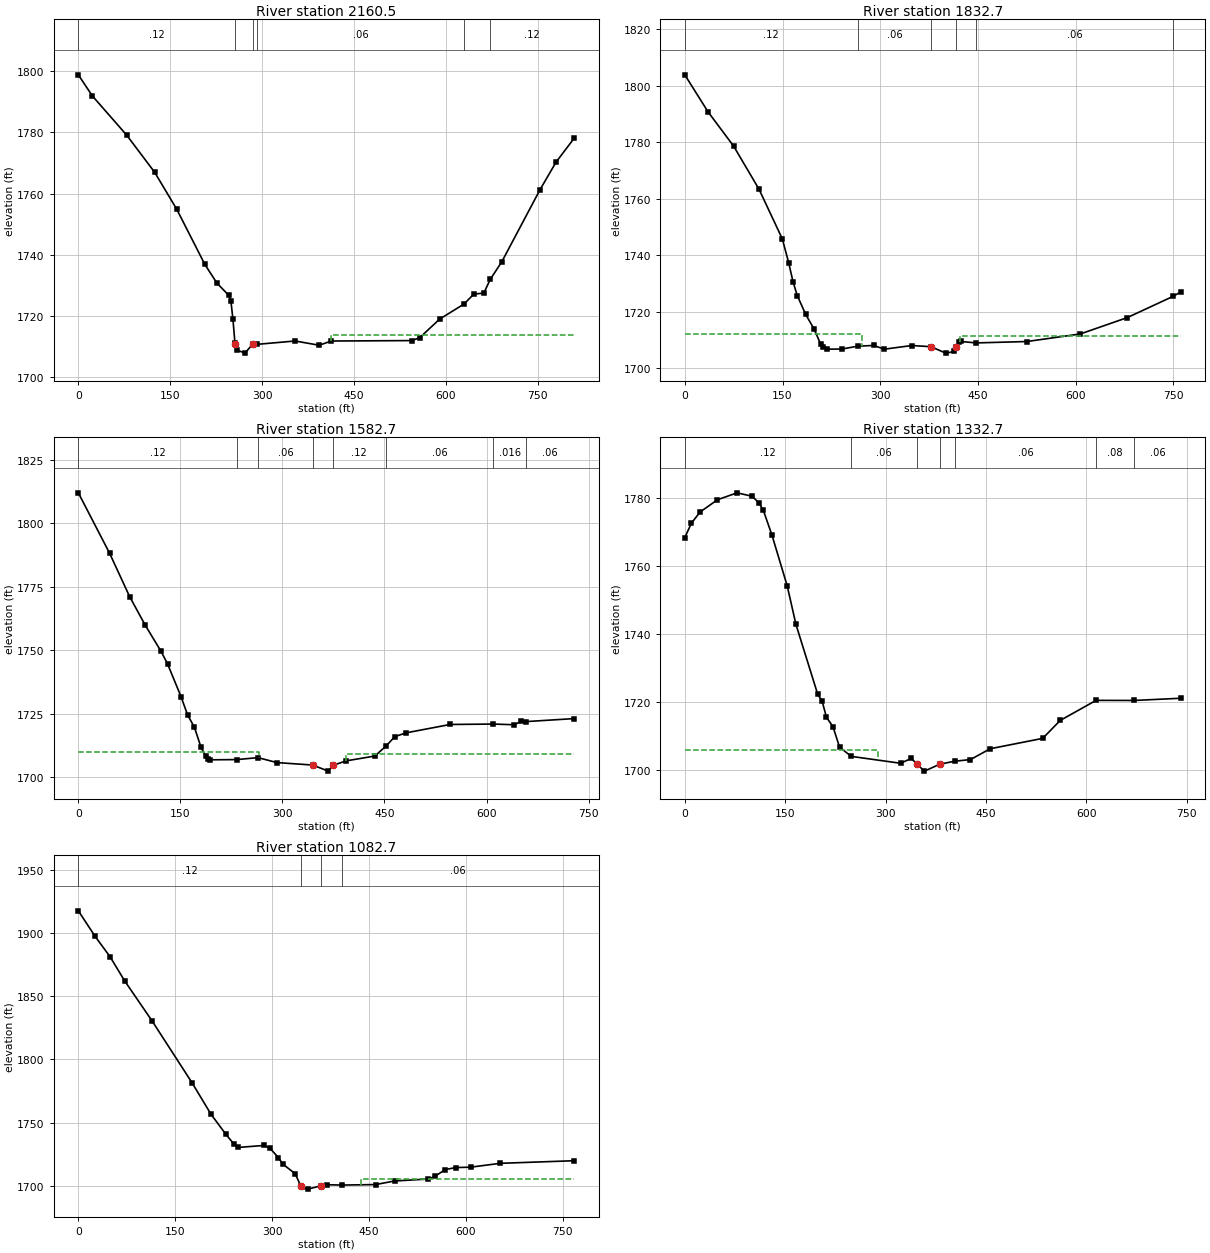
Type RM Length L Ch R = 1 ,2160.5  ,328,327.9,334
XS GIS Cut Line= 2
     2054424.618      179744.911     2054770.973      180476.682
#Sta/Elev= 30
       0 1798.83    22.9 1791.93    78.7 1779.17   124.6 1766.97   160.6  1754.9
   206.5 1736.86   226.2 1730.75   245.8 1726.68   249.1 1724.93   252.4    1719
   255.7 1711.23   256.1 1710.93   258.9 1708.84     272 1707.82   285.2 1710.87
  291.741710.689     354 1711.79   393.3  1710.4     413 1711.78   544.1 1711.92
   557.2 1712.83     590 1718.95  629.84 1723.88   645.7 1727.12   662.1 1727.45
   672.61731.944   691.6 1737.75   753.9 1761.29   780.1  1770.3   809.6 1778.09
#Mann= 6 ,-1 , 0
       0     .12       0   256.1    .045       0   285.2     .12       0
  291.74     .06       0  629.84    .016       0   672.6     .12       0
#XS Ineff= 2 , 0
                           412.8         1713.69
Permanent Ineff=
       F       F
Bank Sta=256.1,285.2
XS Rating Curve= 0 ,0
Exp/Cntr=0.3,0.1

Type RM Length L Ch R = 1 ,1832.7  ,241.8,250,251.2
XS GIS Cut Line= 3
     2054159.855      179859.972     2054343.682      180219.566
     2054392.371      180573.493
#Sta/Elev= 30
       0 1803.86    35.8 1790.71    74.9 1778.63     114 1763.32   149.8 1745.71
   159.6 1737.18   166.1 1730.59   172.6 1725.71   185.6    1719   198.7 1713.74
   208.4 1708.55   211.7 1707.37   218.2 1706.72     241 1706.75  265.741707.787
   289.9 1708.02   306.2 1706.71   348.5    1708   377.8 1707.59   400.6 1705.31
   413.7 1705.89  416.531707.657   420.2 1709.32   423.5 1709.46  446.791708.922
   525.1 1709.42   607.1  1712.1   679.2 1717.89  749.721725.434   761.1 1726.96
#Mann= 6 ,-1 , 0
       0     .12       0  265.74     .06       0   377.8    .045       0
  416.53     .12       0  446.79     .06       0  749.72    .016       0
#XS Ineff= 2 , 0
          272.45 1711.96  422.23         1711.39
Permanent Ineff=
       F       F
Bank Sta=377.8,416.53
XS Rating Curve= 0 ,0
Exp/Cntr=0.3,0.1

Type RM Length L Ch R = 1 ,1582.7  ,247,250,247.9
XS GIS Cut Line= 3
     2054052.863       179878.87     2054096.104      180240.423
     2054122.507      180604.175
#Sta/Elev= 30
       0 1812.06    45.9 1788.28    75.4 1771.18    98.4 1759.87   121.4 1749.69
   131.2 1744.62   150.9 1731.78   160.7 1724.48   170.6 1719.72   180.4 1711.75
     187 1708.47   190.3 1707.26   193.6 1706.87  233.121706.953  264.091707.731
     292 1705.77   344.4 1704.81   367.4 1702.41   373.9 1704.64   393.4 1706.44
   435.8 1708.36  452.121712.239   465.1 1715.98   481.4 1717.47   546.5 1720.79
  609.861720.958   640.9 1720.68   650.7 1722.02  658.651721.933   728.8 1723.11
#Mann= 8 ,-1 , 0
       0     .12       0  233.12     .04       0  264.09     .06       0
   344.4    .045       0   373.9     .12       0  452.12     .06       0
  609.86    .016       0  658.65     .06       0
#XS Ineff= 2 , 0
          265.84 1710.14  393.62         1709.05
Permanent Ineff=
       F       F
Bank Sta=344.4,373.9
XS Rating Curve= 0 ,0
Exp/Cntr=0.3,0.1

Type RM Length L Ch R = 1 ,1332.7  ,259.6,250,239.5
XS GIS Cut Line= 3
     2053849.832      179883.985     2053849.832      180245.285
     2053905.691      180620.453
#Sta/Elev= 30
       0 1768.32     9.8 1772.56    22.8 1775.86    48.8 1779.48    78.1 1781.52
   100.9 1780.49   110.7 1778.52   117.2 1776.42   130.2 1769.06     153 1754.07
     166 1742.76   198.6 1722.13   205.1 1720.15   211.6 1715.39   221.3 1712.64
   231.1 1706.63  248.541703.876   322.2 1701.85   338.5 1703.28  346.671701.582
     358 1699.53   380.9 1701.58  403.251702.453   426.7 1702.93   456.1 1706.12
   534.6 1709.18   560.8 1714.47  614.321720.375  671.111720.348   740.6    1721
#Mann= 7 ,-1 , 0
       0     .12       0  248.54     .06       0  346.67    .045       0
   380.9     .12       0  403.25     .06       0  614.32     .08       0
  671.11     .06       0
#XS Ineff= 2 , 0
           289.3 1705.73
Permanent Ineff=
       F       F
Bank Sta=346.67,380.9
XS Rating Curve= 0 ,0
Exp/Cntr=0.3,0.1

Type RM Length L Ch R = 1 ,1082.7  ,261,250,240.1
XS GIS Cut Line= 3
      2053459.71      179975.031     2053609.391       180297.38
     2053837.886      180640.506
#Sta/Elev= 30
       0 1917.35    26.1 1897.08    48.9 1881.24    71.7 1862.02   114.1 1830.39
   176.1 1781.45   205.4  1756.6   228.2 1740.91   241.3 1732.78   247.8 1730.41
   286.9 1731.94   296.7 1729.73   309.8 1722.31   316.3 1717.34   335.8 1709.58
  344.121700.168   345.6 1698.97   355.4 1697.45     375    1700   384.8 1700.95
  408.061700.653   460.1 1701.05   489.6 1703.88   541.9 1705.42   551.7 1707.46
   568.1 1712.91   584.4  1714.5   607.3 1714.79   653.1 1717.84   767.6  1719.9
#Mann= 4 ,-1 , 0
       0     .12       0  344.12    .045       0     375     .12       0
  408.06     .06       0
#XS Ineff= 2 , 0
                          436.95         1705.17
Permanent Ineff=
       F       F
Bank Sta=344.12,375
XS Rating Curve= 0 ,0
Exp/Cntr=0.3,0.1