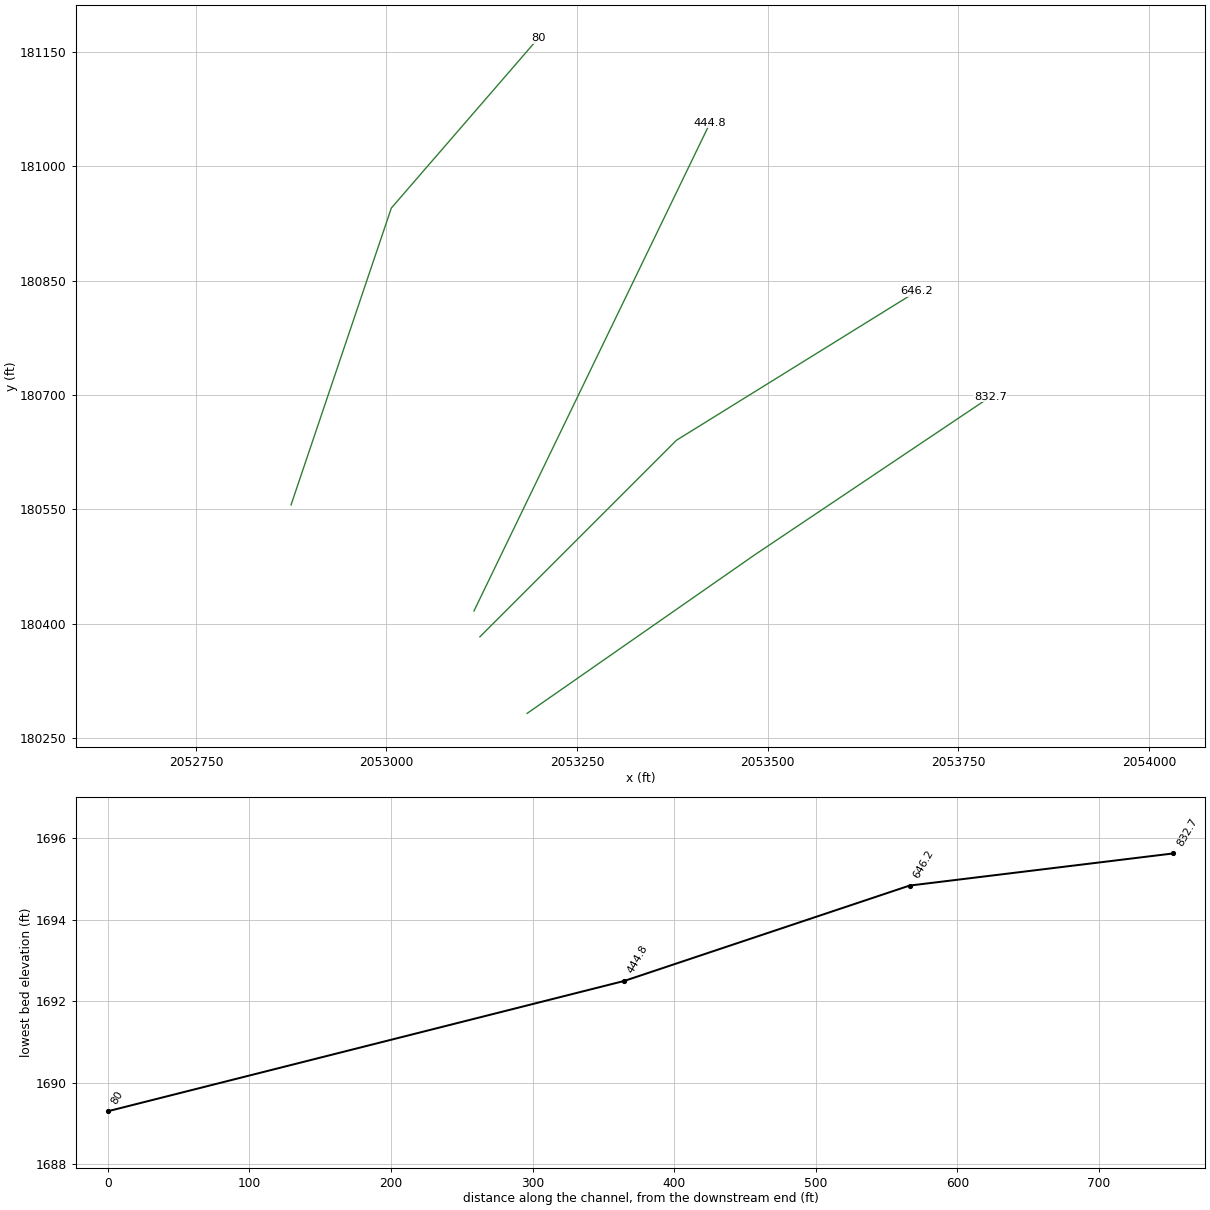
HEC-RAS study BLLKCK.prj: BLLKCK

--- BLLKCK.g01 (geometry) --- (continued)

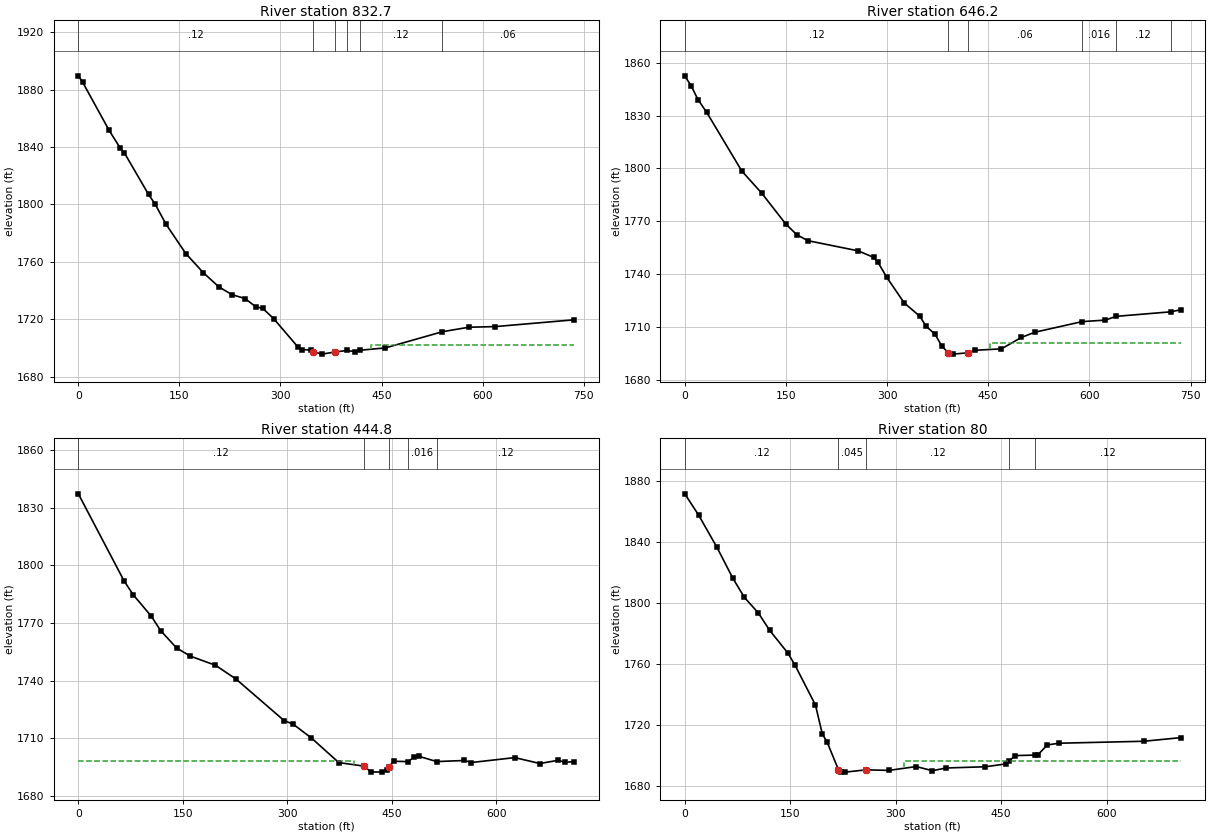
Type RM Length L Ch R = 1 ,832.7   ,187.8,186.4,186.2
XS GIS Cut Line= 3
     2053184.465      180282.498     2053483.638      180490.895
     2053791.969      180697.683
#Sta/Elev= 30
       0 1889.72     6.5 1885.18    45.6 1851.75    61.8 1839.64    68.4 1835.95
   104.2 1806.98   113.9  1800.3   130.2 1786.16   159.5 1765.77   185.6 1752.36
   208.3 1742.63   227.9  1737.1   247.4 1734.41   263.7  1728.5   273.4 1727.66
   289.7 1720.47   325.5 1700.83     332  1698.8   345.1 1698.49   348.3 1697.37
   361.4 1695.63   380.9 1697.11  398.721698.185   410.2 1697.38  417.591698.317
   455.8 1699.98  540.261711.258   579.5 1714.39   618.6 1714.83   735.8 1719.57
#Mann= 6 ,-1 , 0
       0     .12       0   348.3    .045       0   380.9     .12       0
  398.72     .06       0  417.59     .12       0  540.26     .06       0
#XS Ineff= 2 , 0
                          433.65         1702.26
Permanent Ineff=
       F       F
Bank Sta=348.3,380.9
XS Rating Curve= 0 ,0
Exp/Cntr=0.3,0.1

Type RM Length L Ch R = 1 ,646.2   ,188.1,201.4,213.7
XS GIS Cut Line= 3
     2053122.535      180382.932     2053380.348      180640.744
     2053695.452      180836.057
#Sta/Elev= 30
       0  1852.5     9.8 1846.54    19.5 1839.07    32.6 1831.73    84.6 1798.53
   113.9 1786.11   149.8 1768.53     166 1762.53   182.3 1759.13   257.2 1753.34
     280 1749.67   286.5 1746.83   299.5 1738.38   325.5 1723.79   348.3 1716.38
   358.1 1710.54   371.2 1706.08     381 1699.41   390.8 1695.64   397.4 1694.84
   420.4  1695.6   430.2 1697.02   469.6 1697.83   499.1 1704.28   518.8 1707.22
  589.131713.247   623.8 1714.13  639.59 1716.24  720.361718.796   735.3 1719.96
#Mann= 6 ,-1 , 0
       0     .12       0   390.8    .045       0   420.4     .06       0
  589.13    .016       0  639.59     .12       0  720.36     .06       0
#XS Ineff= 2 , 0
                          453.06         1701.09
Permanent Ineff=
       F       F
Bank Sta=390.8,420.4
XS Rating Curve= 0 ,0
Exp/Cntr=0.3,0.1

Type RM Length L Ch R = 1 ,444.8   ,361.1,364.8,366.8
XS GIS Cut Line= 2
     2053114.723      180416.786     2053424.618      181057.411
#Sta/Elev= 30
       0 1837.13    65.6  1791.9    78.7  1784.7   104.9 1773.44   118.1 1766.05
     141 1757.01   160.7 1752.79   196.8 1748.03   226.3 1740.88   295.2 1719.32
   308.3 1717.42   334.5 1710.24   373.9 1697.44   409.9 1695.62   419.8 1692.64
   436.2  1692.5   442.7 1693.61     446 1695.35   452.6 1698.14  473.451697.966
   482.1 1700.45   488.6 1700.75  514.361697.977   554.2 1698.56   564.1 1697.49
   626.4 1700.05   662.4 1696.98   688.7 1698.65   698.5 1697.58   711.6 1698.02
#Mann= 5 ,-1 , 0
       0     .12       0   409.9    .045       0     446     .12       0
  473.45    .016       0  514.36     .12       0
#XS Ineff= 2 , 0
          395.14 1698.31
Permanent Ineff=
       F       F
Bank Sta=409.9,446
XS Rating Curve= 0 ,0
Exp/Cntr=0.3,0.1

Type RM Length L Ch R = 1 ,80      ,83.5,80,76.3
XS GIS Cut Line= 3
     2052874.804      180555.955     2053006.314      180945.278
     2053199.022      181167.934
#Sta/Elev= 30
       0 1871.59    19.6  1857.7    45.7 1836.58    68.5 1816.17    84.8 1803.72
   104.4  1793.7   120.7 1782.19   146.8 1767.19   156.6 1759.52   185.9 1733.24
   195.7 1714.18   202.2 1709.26   218.5 1691.02   221.8 1689.47   228.3  1689.3
   257.6  1690.8   290.3 1690.44   329.4 1692.95   352.2 1690.23   371.8 1692.02
   427.3 1692.81   456.7 1694.65  461.681696.592   469.8 1700.12  497.98 1700.47
   502.6 1700.75   515.6 1707.09     532 1708.23     653 1709.52   705.4 1711.88
#Mann= 5 ,-1 , 0
       0     .12       0   218.5    .045       0   257.6     .12       0
  461.68    .016       0  497.98     .12       0
#XS Ineff= 2 , 0
                          311.63         1696.58
Permanent Ineff=
       F       F
Bank Sta=218.5,257.6
XS Rating Curve= 0 ,0
Exp/Cntr=0.3,0.1

Chan Stop Cuts=-1
Use User Specified Reach Order=0
Composite Channel Slope=5